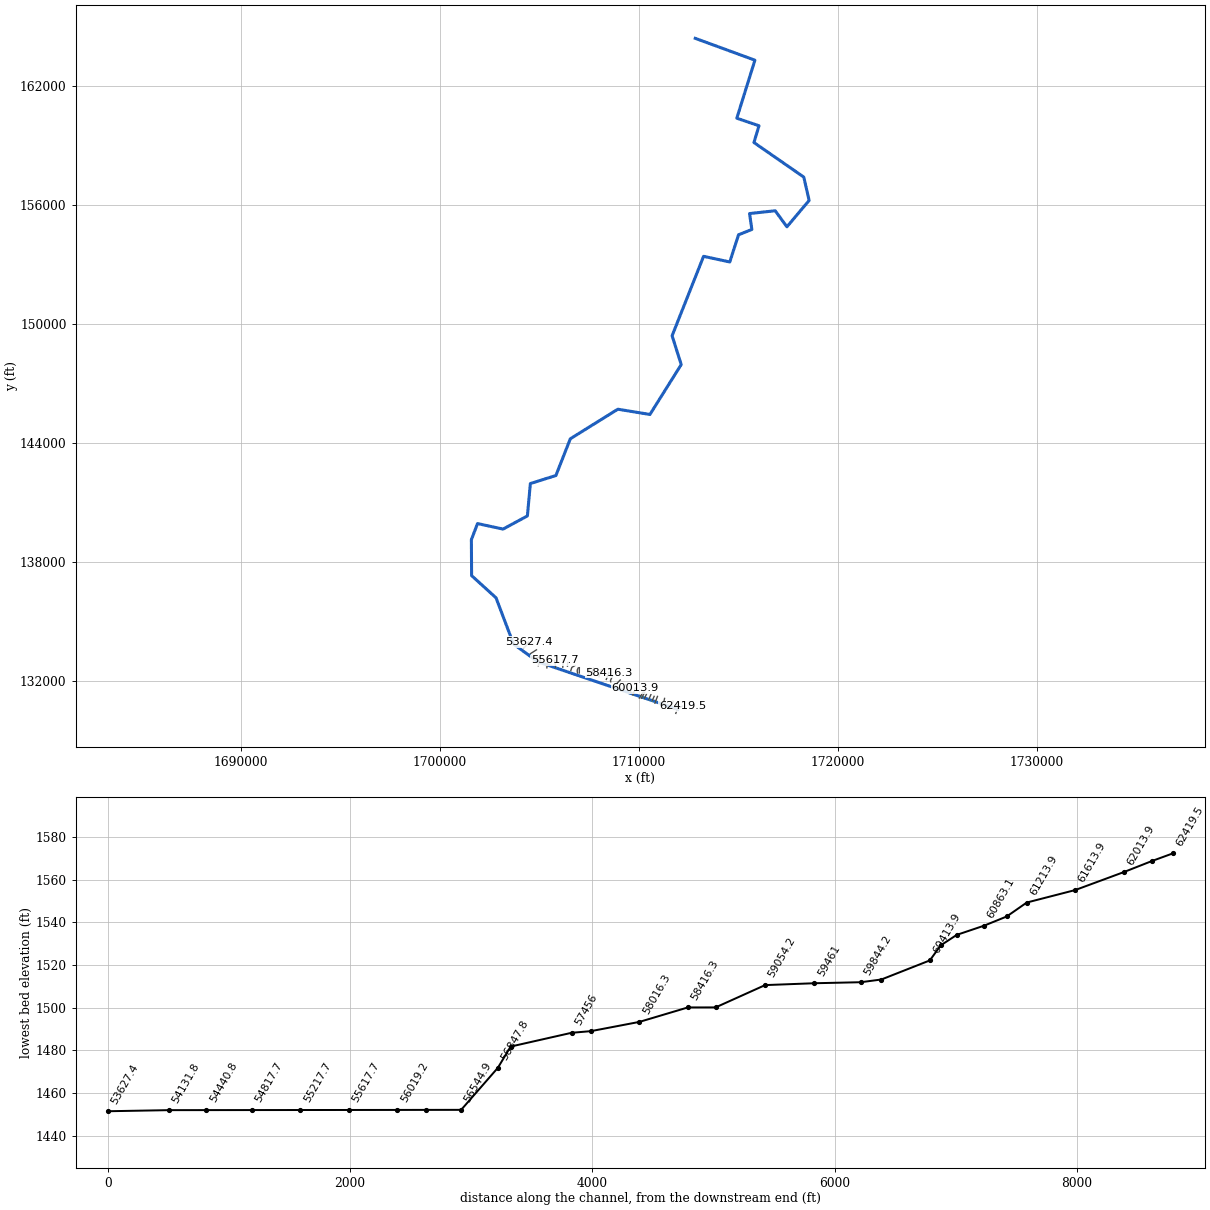
--- Panther Creek.prj (project) ---

Proj Title=Panther Creek
Current Plan=p01
Default Exp/Contr=0,0
English Units
Geom File=g01
Flow File=f01
Plan File=p01
BEGIN DESCRIPTION:
END DESCRIPTION:
DSS Export Rating Curves= 0
DSS Export Rating Curve Sorted= 0
DSS Export Volume Flow Curves= 0
DXF OffsetX= 0
DXF OffsetY= 0
DXF ScaleX= 0
DXF ScaleY= 0

--- Panther Creek.p01 (plan) ---

Plan Title=Floodplain
Program Version=4.00
Geom File=g01
Flow File=f01
K Sum by GR=0
Std Step Tol=0.01
Critical Tol=0.01
Num of Std Step Trials=20
Max Error Tol=0.3
Flow Tol Ratio=0.001
Split Flow NTrial=30
Split Flow Tol=0.02
Split Flow Ratio=0.02
Log Output Level=0
Friction Slope Method=1
Unsteady Friction Slope Method=2
Unsteady Bridges Friction Slope Method=1
Global Log Level=0
CheckData=False
Run HTab=0
Run UNet=0
Run PostProcess=0
UNET Theta=0
UNET Theta Warmup=0
UNET ZTol=0
UNET ZSATol=0
UNET MxIter=0
UNET MaxInSteps=0
UNET DtIC=0
UNET DtMin=0
UNET MaxCRTS=0
UNET WFStab=0
UNET SFStab=0
UNET WFX=0
UNET SFX=0
UNET DSS MLevel=0
UNET DZMax Abort=0
UNET Convert EG Bridges=0
UNET Use Existing IB Tables=0
UNET Froude Limit=0
UNET Froude Power=0
Write IC File=0
Echo Input=False
Echo Output=False
Write Detailed=0

--- Panther Creek.f01 (steady flow) ---

Flow Title=NFF Regression Equation
Program Version=4.00
Number of Profiles=1
Profile Names=P100yr
River Rch & RM=Panther Creek,Main      ,62419.5
504.5011
River Rch & RM=Panther Creek,Main      ,62244.1
626.5714
River Rch & RM=Panther Creek,Main      ,61213.9
669.4210
River Rch & RM=Panther Creek,Main      ,60013.9
737.5988
River Rch & RM=Panther Creek,Main      ,58645.6
813.5755
River Rch & RM=Panther Creek,Main      ,56847.8
873.9540
River Rch & RM=Panther Creek,Main      ,56544.9
1342.517
River Rch & RM=Panther Creek,Main      ,54817.7
1465.742
River Rch & RM=Panther Creek,Main      ,52353.6
1541.313
River Rch & RM=Panther Creek,Main      ,48833.5
1702.781
River Rch & RM=Panther Creek,Main      ,47233.5
1891.137
River Rch & RM=Panther Creek,Main      ,45220.3
2096.118
River Rch & RM=Panther Creek,Main      ,40926.8
2295.680
River Rch & RM=Panther Creek,Main      ,37207.4
2530.229
River Rch & RM=Panther Creek,Main      ,33735.2
2809.305
River Rch & RM=Panther Creek,Main      ,33436.5
3184.269
River Rch & RM=Panther Creek,Main      ,29832.3
3246.270
River Rch & RM=Panther Creek,Main      ,29537.6
4410.163
River Rch & RM=Panther Creek,Main      ,25665.6
4520.642
River Rch & RM=Panther Creek,Main      ,16148.3
4997.639
River Rch & RM=Panther Creek,Main      ,13147.2
5420.559
Boundary for River Rch & Prof#=Panther Creek,Main      ,1
Up Type=0
Dn Type=3
Dn Slope=0.008312

--- Panther Creek.g01 (geometry) ---

Geom Title=Geometry
Program Version=4.00

River Reach=Panther Creek   ,Main
Reach XY= 30
     1711941.928      130592.583     1704911.912      132987.473
     1703688.147      133879.597     1702809.383      136212.001
     1701580.824      137331.838     1701570.162      139142.363
     1701878.811      139954.978     1703163.152      139677.183
     1704385.082      140340.464     1704534.993      141972.966
       1705817.7      142377.289     1706543.108      144229.197
     1708932.514      145721.199     1710544.536      145454.731
     1712117.315      147969.768     1711659.113      149424.189
     1713242.027      153427.846     1714557.529      153142.928
     1715000.027      154514.299     1715668.527      154780.726
     1715551.575      155583.466      1716841.65       155724.24
     1717429.901      154915.922     1718547.275      156244.525
      1718277.88      157422.105     1715772.717      159163.984
     1716027.825      160009.924     1714911.472      160389.524
     1715821.698      163315.106     1712822.332      164416.611

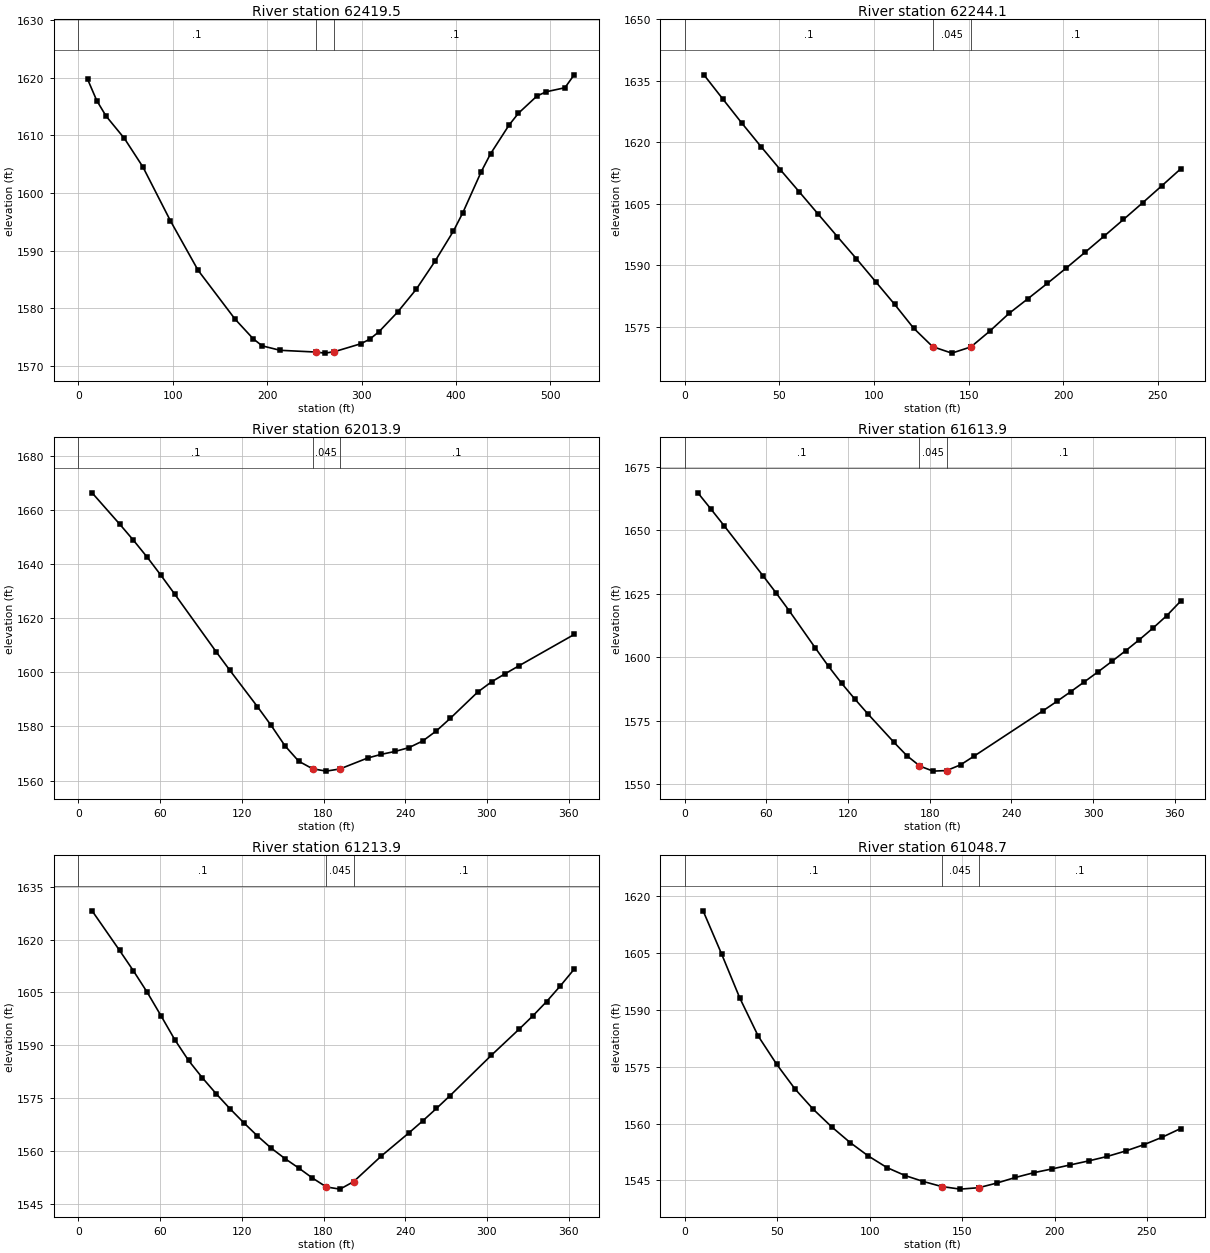
Type RM Length L Ch R = 1 ,62419.5 ,172.8,175.4,177.9
XS GIS Cut Line= 4
     1711844.952      130386.687     1711902.954      130552.598
     1711989.281      130653.763     1712182.169       130752.23
#Sta/Elev= 30
     9.8 1619.73    19.5 1616.03    29.3 1613.36    48.8 1609.47    68.4 1604.53
    97.6 1595.18   126.9 1586.61     166 1578.16   185.3 1574.74   194.8 1573.52
   213.8 1572.75   251.3 1572.45   261.3 1572.26   271.3 1572.51   299.2 1573.88
   308.7 1574.67   318.6 1575.98   338.3 1579.38     358 1583.33   377.7 1588.14
   397.3 1593.39   407.2 1596.54   426.9 1603.72   436.7  1606.8   456.4  1611.8
   466.3 1613.84   485.9 1616.82   495.8 1617.56   515.5 1618.25   525.3 1620.49
#Mann= 3 , 0 , 0
       0      .1       0   251.3    .045       0   271.3      .1       0
Bank Sta=251.3,271.3
XS Rating Curve= 0 ,0
Exp/Cntr=0.3,0.1

Type RM Length L Ch R = 1 ,62244.1 ,231.3,230.2,229.5
XS GIS Cut Line= 2
     1711753.229      130595.762     1711880.023      130825.069
#Sta/Elev= 28
    10.1 1636.47    20.2 1630.51    30.2 1624.66    40.3 1618.95    50.4 1613.38
    60.5 1607.93    70.5  1602.5    80.6 1597.04    90.7 1591.62   100.8 1586.07
   110.9  1580.5   120.9 1574.71     131 1570.18   131.1 1570.17   141.1 1568.62
   151.1 1570.12   151.2 1570.14   161.2    1574   171.3 1578.29   181.4 1581.92
   191.5  1585.6   201.6 1589.38   211.6 1593.24   221.7 1597.19   231.8  1601.2
   241.9 1605.26   251.9 1609.35     262 1613.53
#Mann= 3 , 0 , 0
       0      .1       0   131.1    .045       0   151.1      .1       0
Bank Sta=131.1,151.1
XS Rating Curve= 0 ,0
Exp/Cntr=0.3,0.1

Type RM Length L Ch R = 1 ,62013.9 ,393.9,400,406.8
XS GIS Cut Line= 3
      1711518.95      130668.346     1711615.727      130822.472
     1711709.008      130978.816
#Sta/Elev= 27
    10.1 1666.32    30.3 1654.78    40.4 1648.83    50.6 1642.51    60.7 1635.81
    70.8 1628.86   101.1 1607.64   111.2 1600.76   131.4 1587.36   141.5 1580.41
   151.7 1572.84   161.8 1567.14     172 1564.34     182 1563.48     192 1564.28
   212.3 1568.31   222.4 1569.68   232.6 1570.77   242.7 1572.16   252.8 1574.61
   262.9 1578.37     273 1582.96   293.2  1592.7   303.4 1596.49   313.5 1599.52
   323.6 1602.44     364 1613.97
#Mann= 3 , 0 , 0
       0      .1       0     172    .045       0     192      .1       0
Bank Sta=172,192
XS Rating Curve= 0 ,0
Exp/Cntr=0.3,0.1

Type RM Length L Ch R = 1 ,61613.9 ,402,400,396.8
XS GIS Cut Line= 3
     1711197.278      130786.786     1711243.734      130963.132
      1711279.93      131141.432
#Sta/Elev= 30
     9.6 1664.84    19.2 1658.44    28.8 1651.93    57.6 1632.03    67.2 1625.28
    76.8 1618.27      96 1603.58   105.6 1596.42   115.2 1589.74   124.8  1583.6
   134.4 1577.73   153.6  1566.5   163.2 1561.16   172.4 1557.23   172.8 1557.06
   182.4 1555.09   192.4 1555.32   202.6 1557.57   212.7 1561.06   263.2  1578.9
   273.3 1582.56   283.4 1586.36   293.5 1590.28   303.7 1594.27   313.8 1598.37
   323.9 1602.57     334 1606.93   344.1 1611.55   354.2 1616.45   364.3 1622.11
#Mann= 3 , 0 , 0
       0      .1       0   172.4    .045       0   192.4      .1       0
Bank Sta=172.4,192.4
XS Rating Curve= 0 ,0
Exp/Cntr=0.3,0.1

Type RM Length L Ch R = 1 ,61213.9 ,166.3,165.3,164.2
XS GIS Cut Line= 3
     1710795.483      130902.255     1710859.597      131072.588
     1710923.711      131242.922
#Sta/Elev= 30
    10.1 1628.16    30.3 1616.92    40.4 1611.17    50.6 1605.04    60.7  1598.4
    70.8 1591.62    80.9 1585.73      91 1580.83   101.1 1576.33   111.2 1572.09
   121.3 1568.12   131.4 1564.35   141.6 1560.86   151.7  1557.9   161.8 1555.22
   171.9 1552.38   182.1 1549.85   192.1 1549.24   202.1 1551.36   222.4 1558.62
   242.7 1565.19   252.8 1568.58   262.9 1572.12     273 1575.79   303.3 1587.23
   323.6  1594.6   333.7 1598.38   343.8 1602.44   353.9 1606.89     364 1611.61
#Mann= 3 , 0 , 0
       0      .1       0   182.1    .045       0   202.1      .1       0
Bank Sta=182.1,202.1
XS Rating Curve= 0 ,0
Exp/Cntr=0.3,0.1

Type RM Length L Ch R = 1 ,61048.7 ,185.4,185.6,185.7
XS GIS Cut Line= 2
     1710648.506      131000.422     1710756.415      131245.916
#Sta/Elev= 28
     9.9 1616.03    19.9 1604.67    29.8    1593    39.7 1583.04    49.7  1575.6
    59.6  1569.1    69.5 1563.74    79.5 1559.09    89.4 1554.99    99.3 1551.43
   109.3  1548.4   119.2 1546.28   129.1 1544.71     139 1543.39     149 1542.71
   158.9 1543.08     159 1543.09   168.8 1544.31   178.8 1545.78   188.7 1547.03
   198.6 1548.03   208.6  1549.1   218.5 1550.15   228.4 1551.31   238.4 1552.75
   248.3 1554.41   258.2 1556.38   268.2 1558.67
#Mann= 3 , 0 , 0
       0      .1       0     139    .045       0     159      .1       0
Bank Sta=139,159
XS Rating Curve= 0 ,0
Exp/Cntr=0.3,0.1

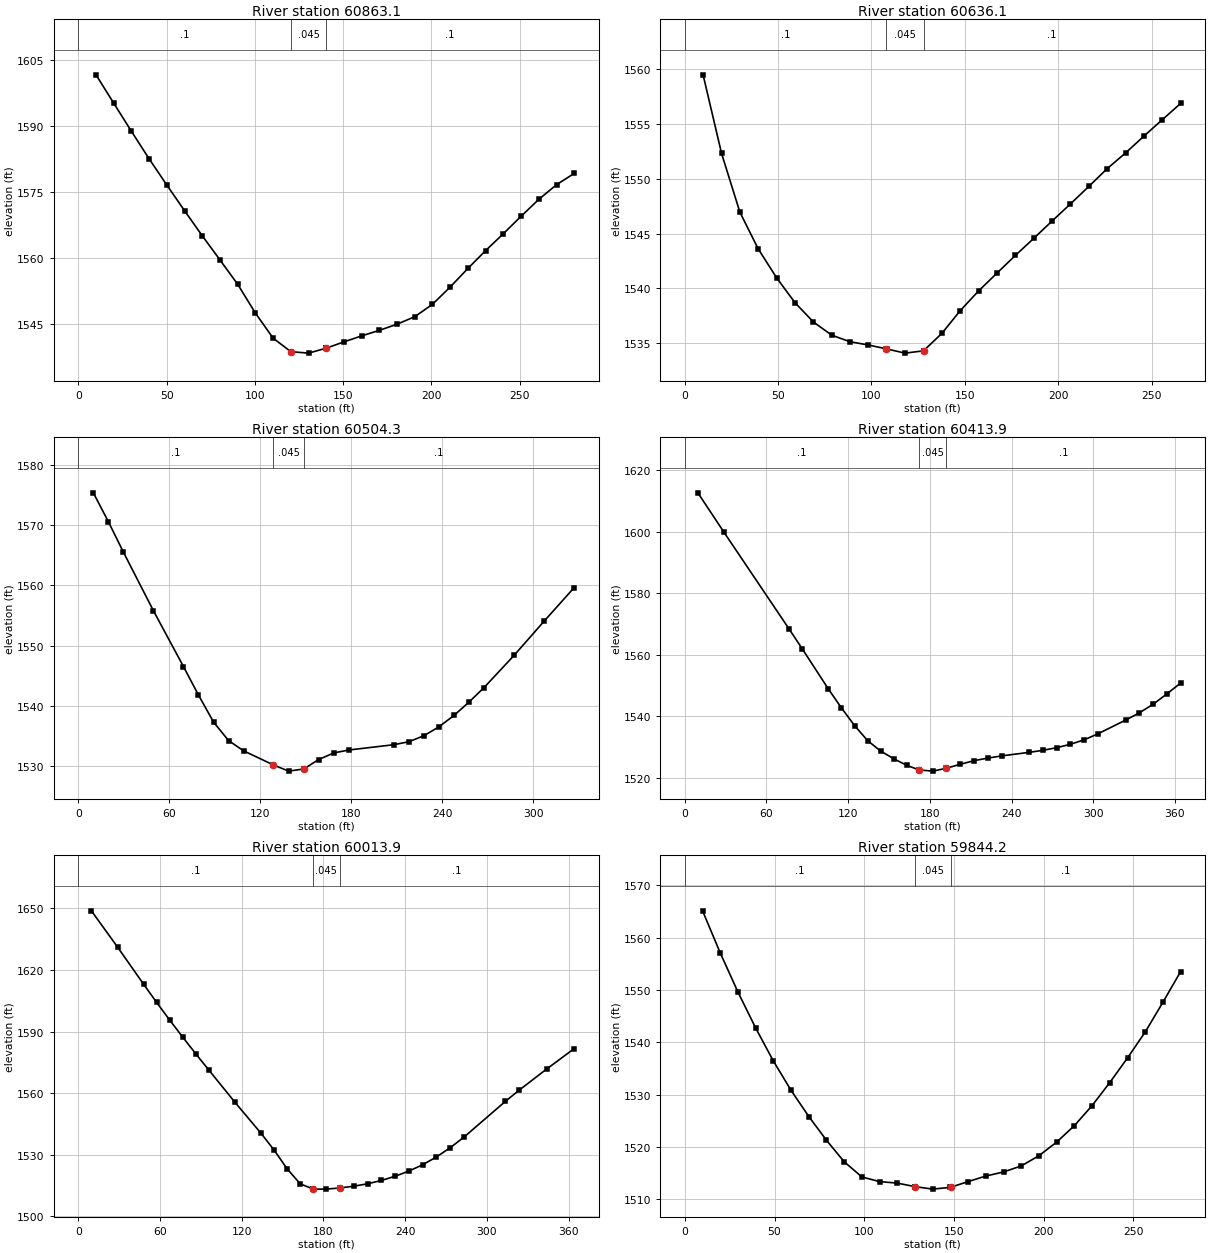
Type RM Length L Ch R = 1 ,60863.1 ,227.1,227,226.8
XS GIS Cut Line= 2
     1710481.246      131075.959     1710593.202      131333.593
#Sta/Elev= 29
      10 1601.59    20.1 1595.13    30.1 1588.76    40.1 1582.53    50.2 1576.54
    60.2 1570.74    70.2 1565.07    80.3 1559.55    90.3 1554.04   100.3 1547.53
   110.4 1541.81   120.4 1538.76   130.4 1538.43   140.4 1539.55   140.5 1539.56
   150.5 1540.99   160.5 1542.34   170.6 1543.61   180.6    1545   190.6  1546.7
   200.6  1549.5   210.7 1553.44   220.7 1557.65   230.7 1561.68   240.8 1565.54
   250.8 1569.47   260.8  1573.3   270.9 1576.65   280.9 1579.21
#Mann= 3 , 0 , 0
       0      .1       0   120.4    .045       0   140.4      .1       0
Bank Sta=120.4,140.4
XS Rating Curve= 0 ,0
Exp/Cntr=0.3,0.1

Type RM Length L Ch R = 1 ,60636.1 ,133.2,131.9,130.5
XS GIS Cut Line= 2
     1710265.427      131127.216     1710376.034      131368.663
#Sta/Elev= 29
     9.8 1559.49    19.7 1552.31    29.5 1546.96    39.3 1543.61    49.2 1540.96
      59  1538.7    68.9 1536.93    78.7 1535.73    88.5 1535.13    98.4 1534.83
     108 1534.48   108.2 1534.47     118 1534.09   127.9  1534.3     128 1534.32
   137.7 1535.89   147.5 1537.96   157.4 1539.77   167.2 1541.39   177.1 1543.01
   186.9 1544.56   196.7 1546.14   206.6 1547.71   216.4  1549.3   226.2 1550.92
   236.1 1552.36   245.9 1553.89   255.7 1555.38   265.6 1556.88
#Mann= 3 , 0 , 0
       0      .1       0     108    .045       0     128      .1       0
Bank Sta=108,128
XS Rating Curve= 0 ,0
Exp/Cntr=0.3,0.1

Type RM Length L Ch R = 1 ,60504.3 ,91.6,90.3,88.1
XS GIS Cut Line= 2
     1710122.171      131151.648     1710278.181      131438.783
#Sta/Elev= 25
     9.9 1575.34    19.8 1570.55    29.7 1565.51    49.5 1555.79    69.3 1546.53
    79.2 1541.81    89.1 1537.34      99 1534.27   108.9 1532.57   128.6 1530.22
   138.6  1529.2   148.6 1529.56   158.4 1531.12   168.3 1532.21   178.2  1532.7
     208 1533.58   217.9 1534.08   227.8 1535.07   237.7 1536.55   247.6 1538.43
   257.5 1540.65   267.4 1543.05   287.2 1548.39     307 1554.06   326.8 1559.62
#Mann= 3 , 0 , 0
       0      .1       0   128.6    .045       0   148.6      .1       0
Bank Sta=128.6,148.6
XS Rating Curve= 0 ,0
Exp/Cntr=0.3,0.1

Type RM Length L Ch R = 1 ,60413.9 ,396.1,400,405.6
XS GIS Cut Line= 3
     1710010.791      131158.268      1710107.82      131312.523
     1710211.677      131461.931
#Sta/Elev= 29
     9.6  1612.7    28.8 1599.86    76.7 1568.33    86.3 1561.92   105.5 1548.83
   115.1 1542.68   124.7 1536.95   134.3 1532.05   143.9 1528.65   153.5 1526.15
   163.1    1524   172.2 1522.51   182.2 1522.13   192.2 1523.07   202.5 1524.38
   212.6 1525.55   222.7 1526.38   232.8 1527.09     253 1528.24   263.1 1528.91
   273.2 1529.76   283.3 1530.87   293.4 1532.33   303.5 1534.28   323.8 1538.74
   333.9  1541.1     344  1543.9   354.1 1547.26   364.2 1550.79
#Mann= 3 , 0 , 0
       0      .1       0   172.2    .045       0   192.2      .1       0
Bank Sta=172.2,192.2
XS Rating Curve= 0 ,0
Exp/Cntr=0.3,0.1

Type RM Length L Ch R = 1 ,60013.9 ,168,169.8,170.8
XS GIS Cut Line= 3
     1709684.304      131318.772     1709749.509      131488.846
     1709808.467      131661.004
#Sta/Elev= 30
     9.6 1648.84    28.8 1631.17    47.9  1613.1    57.5  1604.2    67.1 1595.58
    76.7 1587.23    86.3  1579.1    95.9 1571.17     115 1555.54   134.2 1540.37
   143.8  1532.2   153.4 1523.01     163 1515.74   172.1 1513.33   172.6  1513.2
   182.1 1513.19   192.1 1513.77   202.4 1514.63   212.5 1515.81   222.6 1517.42
   232.7 1519.49   242.8    1522   252.9 1525.09     263 1528.88   273.1 1533.38
   283.2 1538.54   313.6 1555.97   323.7 1561.41   343.9 1571.72   364.1 1581.67
#Mann= 3 , 0 , 0
       0      .1       0   172.1    .045       0   192.1      .1       0
Bank Sta=172.1,192.1
XS Rating Curve= 0 ,0
Exp/Cntr=0.3,0.1

Type RM Length L Ch R = 1 ,59844.2 ,388.2,383.2,378.2
XS GIS Cut Line= 2
     1709550.526      131409.129     1709626.063      131674.857
#Sta/Elev= 30
     9.9 1565.15    19.7 1557.14    29.6 1549.63    39.5 1542.73    49.3 1536.46
    59.2 1530.82    69.1 1525.81    78.9 1521.29    88.8 1517.16    98.7 1514.25
   108.5 1513.36   118.4 1513.07   128.1 1512.41   128.3  1512.4   138.1 1511.92
     148 1512.26   148.1 1512.27   157.9 1513.36   167.7 1514.42   177.6  1515.2
   187.5 1516.36   197.3  1518.3   207.2 1520.91   217.1 1524.06   226.9 1527.87
   236.8 1532.29   246.7 1537.01   256.5 1541.94   266.4 1547.64   276.3 1553.53
#Mann= 3 , 0 , 0
       0      .1       0   128.1    .045       0   148.1      .1       0
Bank Sta=128.1,148.1
XS Rating Curve= 0 ,0
Exp/Cntr=0.3,0.1

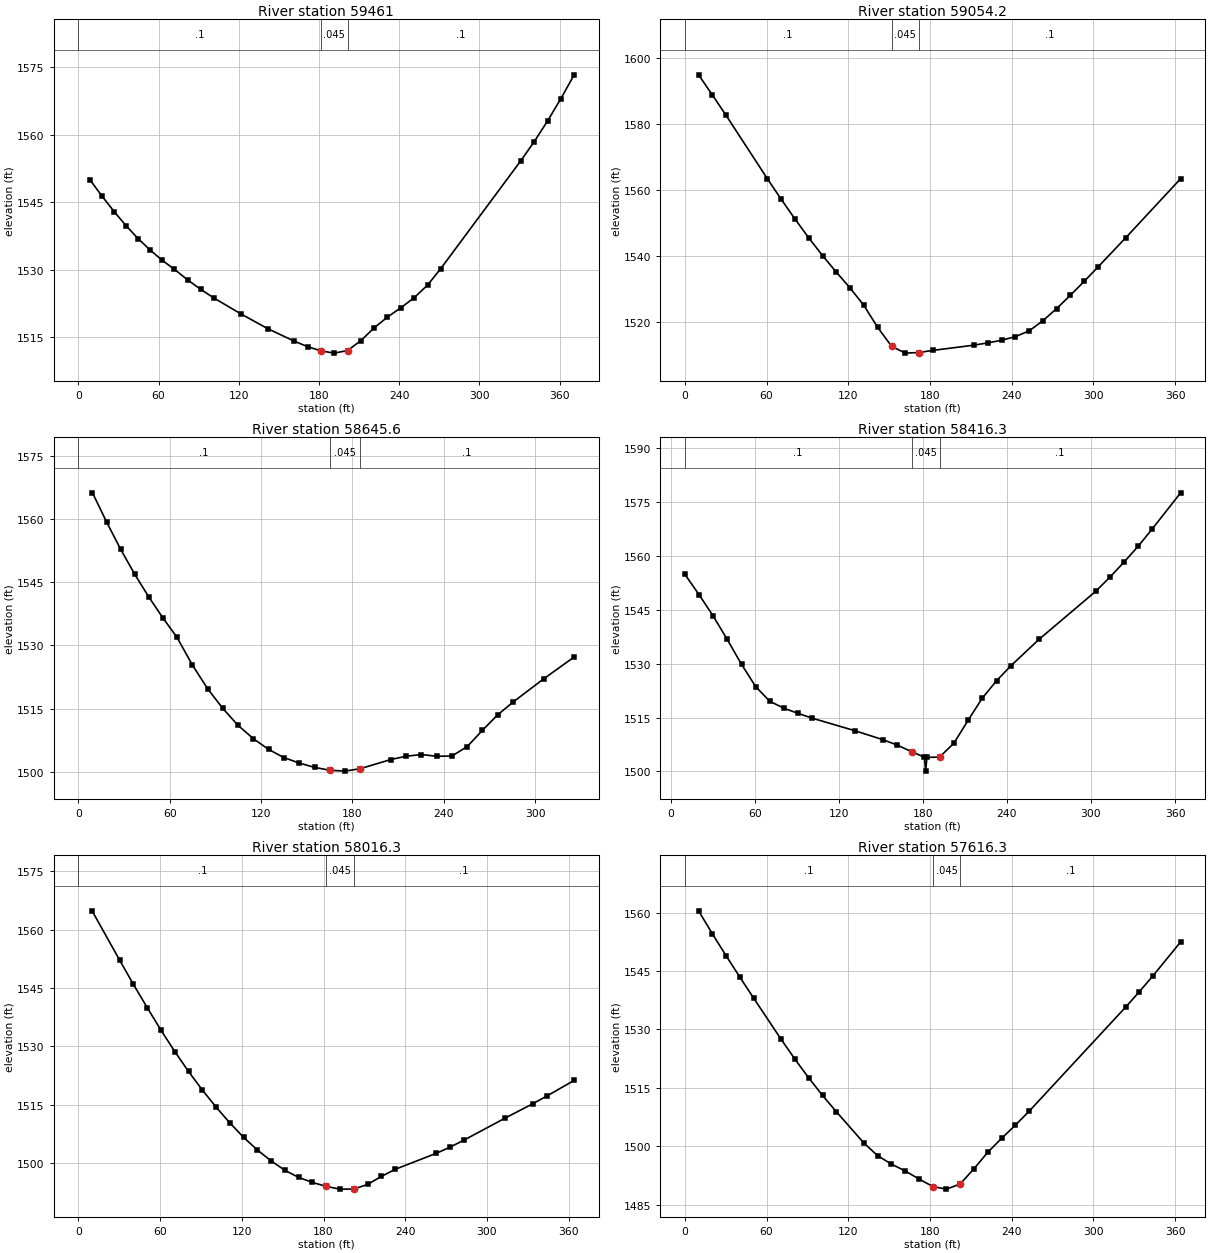
Type RM Length L Ch R = 1 ,59461   ,411.3,406.7,402.2
XS GIS Cut Line= 3
     1709163.401      131514.341     1709178.238      131584.482
     1709327.963      131843.465
#Sta/Elev= 30
       9 1549.82    17.9 1546.24    26.9 1542.85    35.8 1539.71    44.8 1536.85
    53.8 1534.32    62.7 1532.07    71.7 1530.09    81.7 1527.72    91.6 1525.59
   101.6 1523.65   121.6 1520.15   141.5  1516.9   161.4 1514.11   171.4 1512.88
   181.4 1511.95   191.4 1511.44   201.4 1512.02   211.3 1514.22   221.3 1517.07
   231.2 1519.45   241.2 1521.52   251.2 1523.76   261.2 1526.57   271.1 1530.24
     331 1554.22   340.9 1558.42   350.9 1563.01   360.9    1568   370.8 1573.27
#Mann= 3 , 0 , 0
       0      .1       0   181.4    .045       0   201.4      .1       0
Bank Sta=181.4,201.4
XS Rating Curve= 0 ,0
Exp/Cntr=0.3,0.1

Type RM Length L Ch R = 1 ,59054.2 ,402.1,408.6,415.1
XS GIS Cut Line= 3
     1708800.578      131804.063     1708925.265      131936.642
     1709049.953       132069.22
#Sta/Elev= 28
    10.1 1594.93    20.2 1588.85    30.3 1582.64    60.7 1563.38    70.8 1557.19
    80.9 1551.22      91  1545.5   101.1 1540.15   111.2 1535.14   121.3 1530.34
   131.4 1525.07   141.6 1518.37   151.8 1512.65   161.8 1510.57   171.8 1510.76
     182 1511.39   212.3 1512.99   222.4 1513.67   232.6 1514.48   242.7 1515.57
   252.8 1517.32   262.9  1520.4     273 1524.09   283.1 1528.12   293.2 1532.33
   303.3 1536.66   323.6  1545.5     364 1563.45
#Mann= 3 , 0 , 0
       0      .1       0   151.8    .045       0   171.8      .1       0
Bank Sta=151.8,171.8
XS Rating Curve= 0 ,0
Exp/Cntr=0.3,0.1

Type RM Length L Ch R = 1 ,58645.6 ,227.9,229.3,230.8
XS GIS Cut Line= 3
     1708575.294      131979.701     1708561.805      132043.098
     1708669.715      132280.499
#Sta/Elev= 30
     9.3  1566.3    18.5 1559.41    27.8 1552.87      37 1546.95    46.3 1541.52
    55.6 1536.52    64.8 1531.92    74.8 1525.42    84.9 1519.72    94.9 1515.02
   104.9    1511     115 1507.82     125 1505.27     135 1503.34   145.1 1502.03
   155.1 1501.02   165.1 1500.33   175.1 1500.12   185.1  1500.7   205.2 1502.88
   215.3 1503.66   225.3 1504.07   235.3 1503.65   245.4 1503.72   255.4 1505.97
   265.4 1509.83   275.4 1513.51   285.5 1516.55   305.5 1522.04   325.6 1527.26
#Mann= 3 , 0 , 0
       0      .1       0   165.1    .045       0   185.1      .1       0
Bank Sta=165.1,185.1
XS Rating Curve= 0 ,0
Exp/Cntr=0.3,0.1

Type RM Length L Ch R = 1 ,58416.3 ,399.1,400,400.9
XS GIS Cut Line= 3
     1708351.377      132098.036     1708414.694      132268.668
      1708478.01      132439.299
#Sta/Elev= 30
    10.1 1554.92    20.2 1549.27    30.3 1543.32    40.4 1536.75    50.6 1529.82
    60.7 1523.62    70.8 1519.53    80.9 1517.61      91 1516.16   101.1 1514.84
   131.4 1511.36   151.7 1508.83   161.8 1507.34     172  1505.5  181.16 1503.98
     182  1500.1  182.93 1503.92     192 1504.02   202.2 1507.89   212.3 1514.26
   222.4  1520.4   232.6 1525.25   242.7 1529.38   262.9 1536.77   303.3 1550.13
   313.4 1554.05   323.6 1558.29   333.7 1562.71   343.8 1567.56     364 1577.58
#Mann= 3 , 0 , 0
    10.1      .1       0     172    .045       0     192      .1       0
Bank Sta=172,192
XS Rating Curve= 0 ,0
Exp/Cntr=0.3,0.1

Type RM Length L Ch R = 1 ,58016.3 ,399.7,400,400.3
XS GIS Cut Line= 3
     1707982.256      132229.913     1708038.193      132403.103
     1708094.131      132576.294
#Sta/Elev= 29
    10.1 1564.86    30.3  1552.2    40.4 1545.98    50.6 1539.96    60.7 1534.17
    70.8 1528.69    80.9 1523.57      91 1518.82   101.1 1514.43   111.2 1510.36
   121.3 1506.65   131.4  1503.4   141.6 1500.56   151.7 1498.16   161.8 1496.33
   171.9 1495.05   182.1 1494.02   192.1 1493.33   202.1 1493.34   212.3 1494.53
   222.4 1496.58   232.6 1498.42   262.9 1502.55     273 1504.14   283.1 1505.92
   313.4  1511.6   333.7 1515.29   343.8 1517.23     364 1521.28
#Mann= 3 , 0 , 0
       0      .1       0   182.1    .045       0   202.1      .1       0
Bank Sta=182.1,202.1
XS Rating Curve= 0 ,0
Exp/Cntr=0.3,0.1

Type RM Length L Ch R = 1 ,57616.3 ,157.4,160.3,163.3
XS GIS Cut Line= 3
      1707597.65      132320.006     1707650.899      132494.042
     1707704.149      132668.078
#Sta/Elev= 27
    10.1 1560.47    20.2  1554.6    30.3 1548.94    40.4 1543.45    50.6 1538.02
    70.8 1527.43    80.9 1522.35      91 1517.55   101.1 1513.07   111.2  1508.9
   131.4 1500.87   141.6 1497.57   151.7 1495.43   161.8 1493.66   171.9 1491.61
   182.1 1489.66   192.1    1489   202.1 1490.31   212.3 1494.23   222.4 1498.46
   232.6 1502.05   242.7 1505.44   252.8 1509.01   323.6 1535.73   333.7  1539.7
   343.8 1543.83     364 1552.48
#Mann= 3 , 0 , 0
       0      .1       0   182.1    .045       0   202.1      .1       0
Bank Sta=182.1,202.1
XS Rating Curve= 0 ,0
Exp/Cntr=0.3,0.1

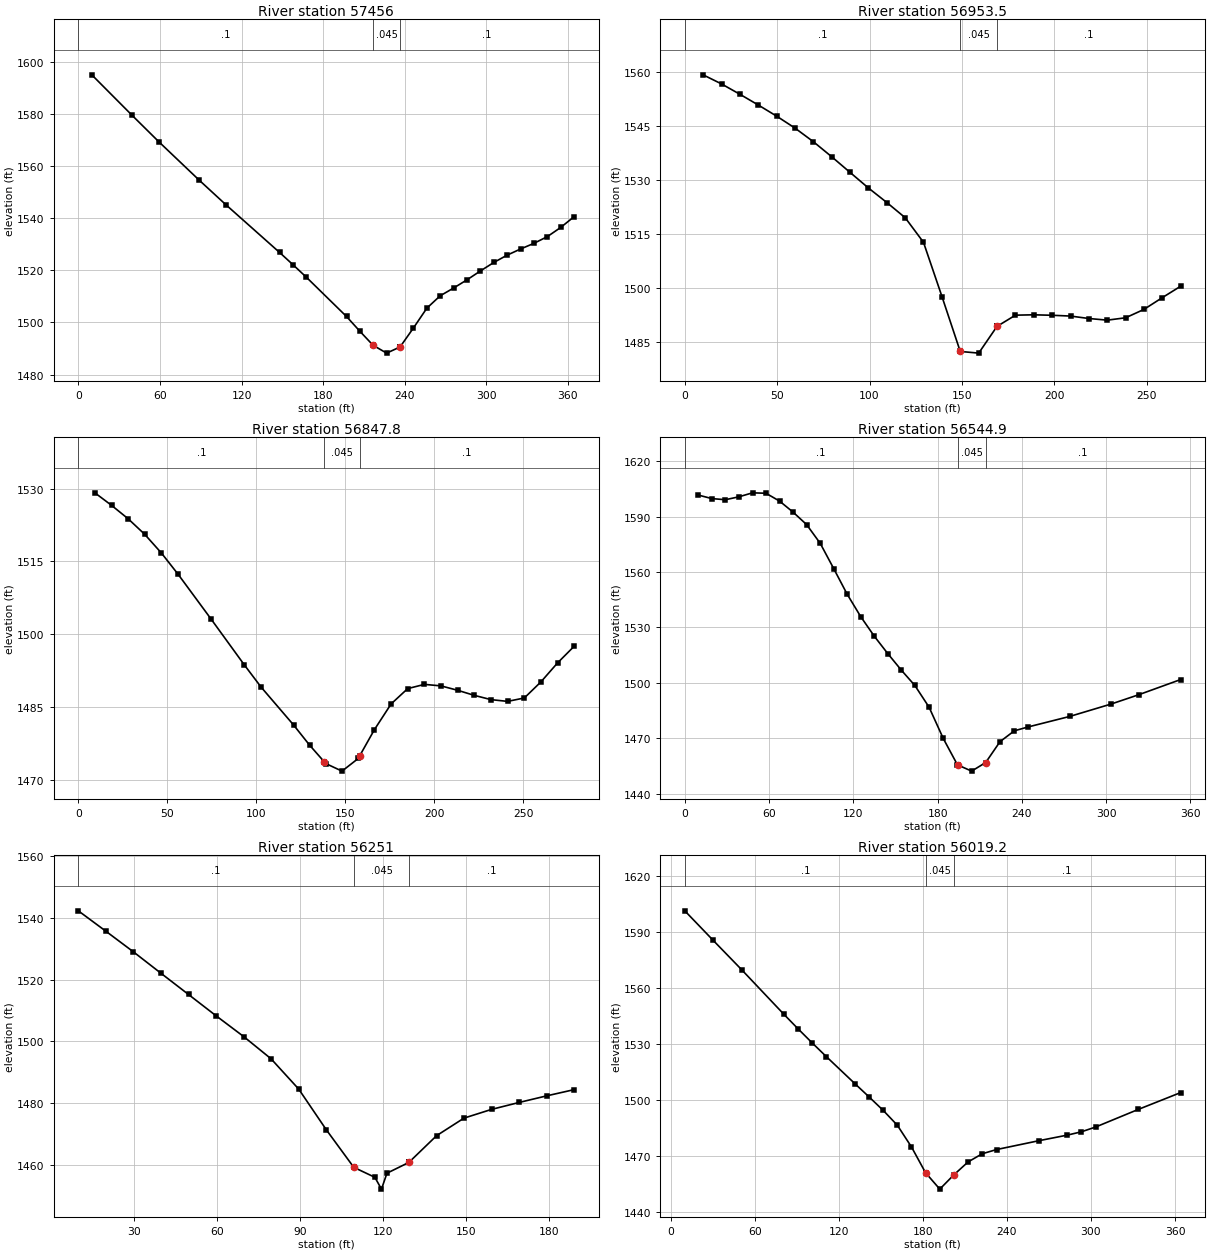
Type RM Length L Ch R = 1 ,57456   ,499.7,502.5,505.2
XS GIS Cut Line= 3
     1707453.004      132311.427      1707470.57      132368.175
     1707516.099      132669.917
#Sta/Elev= 27
     9.9 1595.03    39.6 1579.45    59.4 1569.24    88.9 1554.59   108.6 1545.13
     148 1526.85   157.8 1522.17   167.7 1517.34   197.2 1502.28   207.1 1496.57
   216.7 1491.25   226.7 1488.22   236.6 1490.59   236.7 1490.67   246.4 1497.86
   256.3 1505.49   266.1 1510.23     276 1513.22   285.8 1516.35   295.7 1519.77
   305.5 1523.01   315.3 1525.82   325.2 1528.19     335 1530.35   344.9 1532.94
   354.7 1536.45   364.6 1540.61
#Mann= 3 , 0 , 0
       0      .1       0   216.7    .045       0   236.7      .1       0
Bank Sta=216.7,236.7
XS Rating Curve= 0 ,0
Exp/Cntr=0.3,0.1

Type RM Length L Ch R = 1 ,56953.5 ,107.1,105.7,103.6
XS GIS Cut Line= 2
     1706995.768       132422.13     1706997.117      132690.555
#Sta/Elev= 28
     9.9 1559.33    19.9 1556.79    29.8 1553.92    39.8 1550.91    49.7 1547.82
    59.7 1544.47    69.6 1540.69    79.5 1536.51    89.5 1532.12    99.4 1527.79
   109.4 1523.73   119.3 1519.51   129.2 1512.66   139.2 1497.55   149.1 1482.24
   159.1 1481.77     169 1489.22   169.1 1489.25     179 1492.35   188.9 1492.45
   198.8 1492.32   208.8  1492.1   218.7 1491.42   228.7 1490.96   238.6 1491.62
   248.5 1493.94   258.5 1497.24   268.4 1500.41
#Mann= 3 , 0 , 0
       0      .1       0   149.1    .045       0   169.1      .1       0
Bank Sta=149.1,169.1
XS Rating Curve= 0 ,0
Exp/Cntr=0.3,0.1

Type RM Length L Ch R = 1 ,56847.8 ,320.8,302.9,285.7
XS GIS Cut Line= 4
     1706906.651      132416.735     1706889.116        132517.9
     1706894.511      132581.297     1706943.071      132682.462
#Sta/Elev= 29
     9.3 1529.11    18.7 1526.52      28 1523.76    37.3 1520.56    46.7  1516.7
      56 1512.36    74.7 1503.05    93.3 1493.65   102.7 1489.09   120.9 1481.31
   129.9 1477.16   138.1 1473.74     139 1473.37   148.1 1471.81   157.2 1474.41
   158.1    1475   166.3 1480.35   175.7 1485.65     185  1488.8   194.4 1489.67
   203.7 1489.36   213.1 1488.45   222.4 1487.41   231.8 1486.53   241.1 1486.17
   250.5 1486.87   259.8 1490.17   269.2  1494.1   278.5 1497.52
#Mann= 3 , 0 , 0
       0      .1       0   138.1    .045       0   158.1      .1       0
Bank Sta=138.1,158.1
XS Rating Curve= 0 ,0
Exp/Cntr=0.3,0.1

Type RM Length L Ch R = 1 ,56544.9 ,275.7,293.9,312.2
XS GIS Cut Line= 4
     1706568.177      132542.179     1706616.736      132698.648
     1706674.738      132739.114     1706777.252      132798.464
#Sta/Elev= 30
     9.6 1601.69    19.3 1599.77    28.9 1599.17    38.5 1600.74    48.2  1602.9
    57.8 1602.67    67.5  1598.4    77.1 1592.43    86.7 1585.71    96.4 1575.55
     106 1561.87   115.6 1547.97   125.3 1535.76   134.9 1525.23   144.6 1515.71
   154.2  1506.8   163.8 1498.52   173.9 1486.78     184 1469.84   194.1 1455.55
   194.2 1455.52   204.2 1452.13   214.2 1456.77   224.4 1468.08   234.6 1473.97
   244.4 1476.06     274 1481.75   303.7 1488.52   323.4 1493.58     353 1501.74
#Mann= 3 , 0 , 0
       0      .1       0   194.2    .045       0   214.2      .1       0
Bank Sta=194.2,214.2
XS Rating Curve= 0 ,0
Exp/Cntr=0.3,0.1

Type RM Length L Ch R = 1 ,56251   ,231.9,231.8,231.7
XS GIS Cut Line= 2
     1706399.568      132766.092     1706410.359      132954.933
#Sta/Elev= 22
      10 1542.26    19.9 1535.69    29.9 1528.97    39.8 1522.07    49.8 1515.16
    59.7  1508.3    69.7 1501.55    79.6 1494.34    89.6 1484.52    99.6  1471.3
   109.5 1459.17  117.11 1455.94   119.5 1452.11  121.48 1457.27   129.4 1460.76
   129.5 1460.85   139.4 1469.42   149.3 1475.11   159.3 1477.95   169.2 1480.18
   179.2 1482.33   189.1 1484.34
#Mann= 3 , 0 , 0
      10      .1       0   109.5    .045       0   129.5      .1       0
Bank Sta=109.5,129.5
XS Rating Curve= 0 ,0
Exp/Cntr=0.3,0.1

Type RM Length L Ch R = 1 ,56019.2 ,397.5,401.5,405.5
XS GIS Cut Line= 3
     1706164.156      132715.952      1706175.37      132897.607
     1706186.583      133079.261
#Sta/Elev= 25
    10.1 1601.11    30.3 1585.34    50.6 1569.65    80.9 1545.65      91 1537.88
   101.1 1530.32   111.2 1522.99   131.4 1508.64   141.6 1501.49   151.7 1494.26
   161.8  1486.3   171.9 1474.67     182 1460.79   182.1 1460.73   192.1 1452.09
   202.1  1459.7   212.3 1466.66   222.4 1471.03   232.6 1473.28   262.9 1478.03
   283.1 1481.01   293.2 1482.79   303.3 1485.34   333.7 1494.75     364 1503.78
#Mann= 3 , 0 , 0
    10.1      .1       0   182.1    .045       0   202.1      .1       0
Bank Sta=182.1,202.1
XS Rating Curve= 0 ,0
Exp/Cntr=0.3,0.1

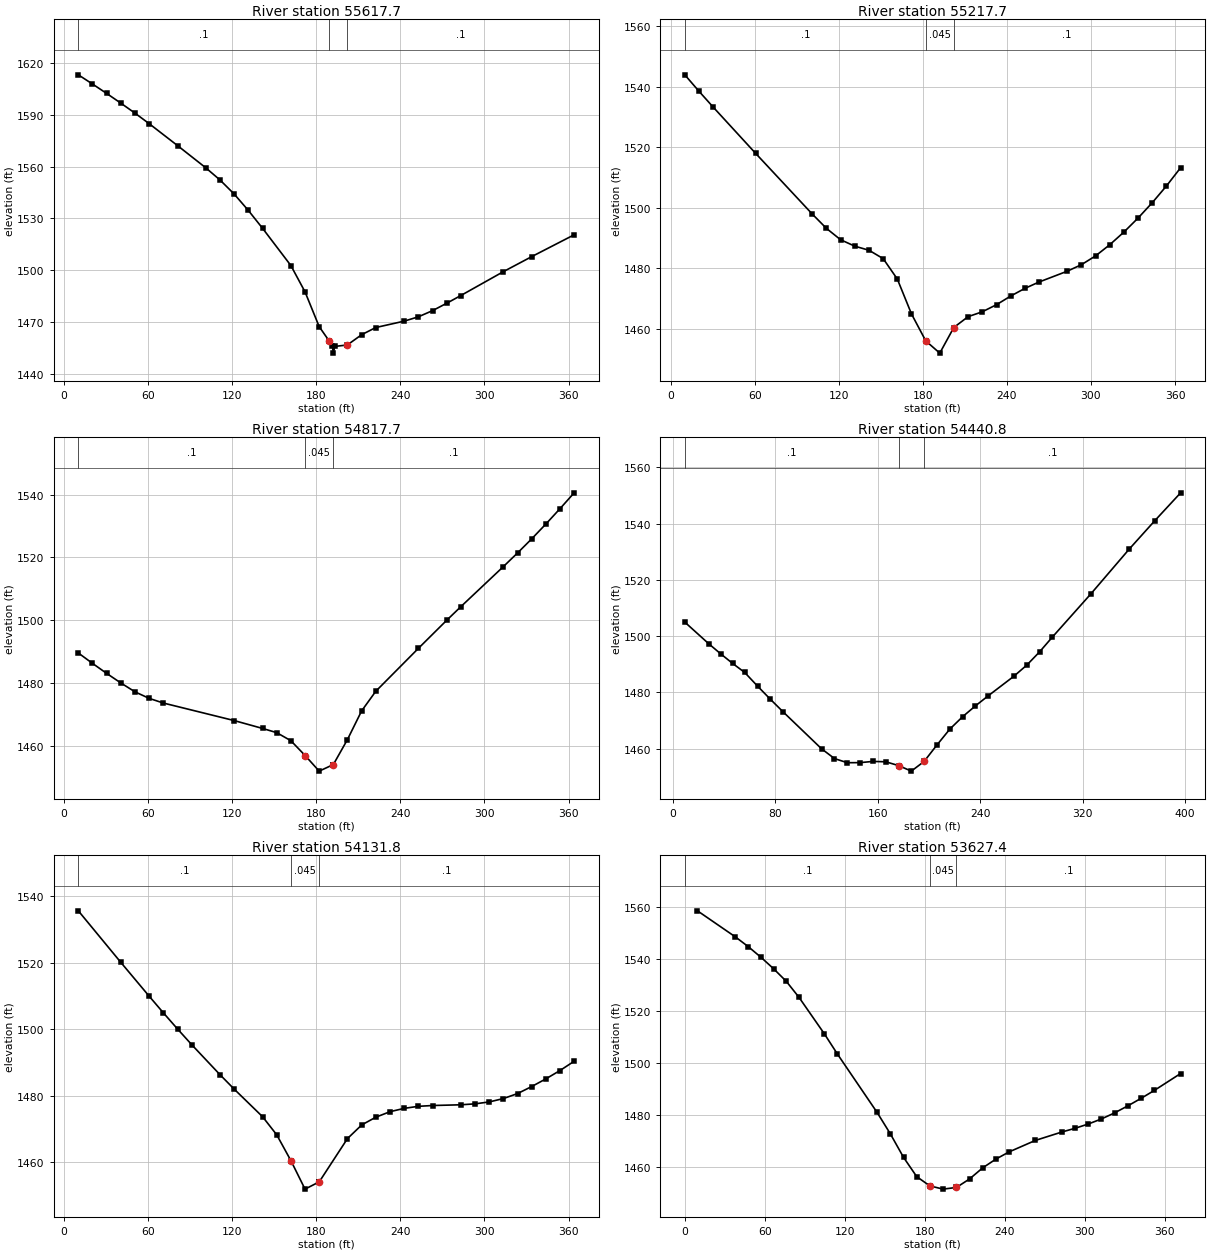
Type RM Length L Ch R = 1 ,55617.7 ,404.4,399.9,395.4
XS GIS Cut Line= 3
     1705803.584      132698.394      1705778.24       132878.62
     1705752.896      133058.847
#Sta/Elev= 30
    10.1 1613.14    20.2 1607.82    30.3 1602.38    40.4 1596.77    50.6 1590.93
    60.7 1584.85    80.9 1572.19   101.1  1559.3   111.2  1552.3   121.3 1544.17
   131.4  1534.7   141.6 1524.31   161.8 1502.77   171.9 1487.54     182 1467.42
  188.92 1459.35   191.4  1456.4   192.1 1452.07  193.14 1455.96   202.1 1456.78
   212.3 1462.73   222.4 1466.89   242.7 1470.58   252.8 1473.09   262.9 1476.65
     273 1480.92   283.1  1485.4   313.4 1499.19   333.7 1507.92     364 1520.56
#Mann= 3 , 0 , 0
    10.1      .1       0  188.92    .045       0   202.1      .1       0
Bank Sta=188.92,202.1
XS Rating Curve= 0 ,0
Exp/Cntr=0.3,0.1

Type RM Length L Ch R = 1 ,55217.7 ,405.6,400,394.4
XS GIS Cut Line= 3
     1705364.558      132681.669     1705380.223      132862.993
     1705395.889      133044.318
#Sta/Elev= 30
    10.1 1543.86    20.2 1538.45    30.3 1533.24    60.7 1517.93   101.1 1497.92
   111.2  1493.2   121.3 1489.46   131.4 1487.34   141.6 1485.98   151.7 1483.22
   161.8 1476.48   171.9 1464.98   182.1 1456.08   192.1 1452.05   202.1  1460.5
   212.3 1464.08   222.4 1465.68   232.6 1468.03   242.7 1470.88   252.8  1473.4
   262.9  1475.5   283.1 1479.08   293.2 1481.23   303.3 1484.13   313.4  1487.8
   323.6 1492.02   333.7 1496.65   343.8  1501.7   353.9 1507.21     364 1513.22
#Mann= 3 , 0 , 0
    10.1      .1       0   182.1    .045       0   202.1      .1       0
Bank Sta=182.1,202.1
XS Rating Curve= 0 ,0
Exp/Cntr=0.3,0.1

Type RM Length L Ch R = 1 ,54817.7 ,399.9,376.9,353.9
XS GIS Cut Line= 3
      1704929.71      132788.643     1704995.044      132958.512
     1705060.378      133128.381
#Sta/Elev= 27
    10.1 1489.62    20.2 1486.31    30.3 1483.13    40.4 1480.09    50.6 1477.24
    60.7 1475.17    70.8 1473.69   121.3 1468.12   141.6 1465.61   151.7 1464.27
   161.8 1461.71     172 1456.98     182 1452.03     192 1454.09   192.1 1454.11
   202.2 1462.09   212.3 1471.19   222.4 1477.43   252.8 1491.08     273 1500.01
   283.1 1504.34   313.4 1517.07   323.6 1521.44   333.7 1525.93   343.8 1530.64
   353.9 1535.53     364 1540.57
#Mann= 3 , 0 , 0
    10.1      .1       0     172    .045       0     192      .1       0
Bank Sta=172,192
XS Rating Curve= 0 ,0
Exp/Cntr=0.3,0.1

Type RM Length L Ch R = 1 ,54440.8 ,299.9,309,318.3
XS GIS Cut Line= 3
     1704600.434      133220.541     1704641.992      133182.892
     1704980.558      133217.963
#Sta/Elev= 30
     9.3 1504.97      28 1497.28    37.4 1493.67    46.7 1490.27    56.1 1487.07
    66.1 1482.23    76.1 1477.56    86.1 1473.06   116.1 1459.95   126.2 1456.47
   136.2    1455   146.2 1455.03   156.2 1455.46   166.2 1455.33   176.2 1453.99
   186.2 1452.01   196.2 1455.46   206.2  1461.3   216.3 1466.96   226.3 1471.37
   236.3 1475.21   246.3  1478.8   266.3 1485.74   276.3 1489.66   286.3 1494.37
   296.3 1499.63   326.4    1515   356.4 1530.94   376.4 1541.05   396.5 1550.92
#Mann= 3 , 0 , 0
     9.3      .1       0   176.2    .045       0   196.2      .1       0
Bank Sta=176.2,196.2
XS Rating Curve= 0 ,0
Exp/Cntr=0.3,0.1

Type RM Length L Ch R = 1 ,54131.8 ,496,504.4,512.7
XS GIS Cut Line= 3
     1704533.222      133394.615      1704687.55      133491.124
     1704840.573      133589.647
#Sta/Elev= 30
    10.1 1535.54    40.4 1520.08    60.7 1509.89    70.8 1504.91    80.9 1500.07
      91 1495.37   111.2 1486.35   121.3 1482.03   141.6 1473.73   151.7  1468.3
   161.9 1460.48   171.9 1451.99   181.9 1454.14     182 1454.14   202.2 1467.17
   212.4 1471.27   222.5  1473.6   232.6 1475.24   242.7 1476.24   252.8 1476.85
   262.9 1477.09   283.1 1477.31   293.2 1477.59   303.4 1478.17   313.5 1479.18
   323.6 1480.68   333.7 1482.79   343.8 1485.09   353.9  1487.6     364 1490.38
#Mann= 3 , 0 , 0
    10.1      .1       0   161.9    .045       0   181.9      .1       0
Bank Sta=161.9,181.9
XS Rating Curve= 0 ,0
Exp/Cntr=0.3,0.1

Type RM Length L Ch R = 1 ,53627.4 ,472.3,482.2,492
XS GIS Cut Line= 3
     1704206.355      133703.026     1704293.984      133760.208
     1704442.512      133982.256
#Sta/Elev= 30
     9.5 1558.41      38 1548.37    47.6 1544.64    57.1 1540.57    66.6 1536.15
    76.1 1531.33    85.6 1525.19   104.6 1511.19   114.5 1503.34   144.2 1480.95
   154.1 1472.75     164 1463.71   173.9 1456.29   183.7 1452.73   193.7 1451.48
   203.7 1452.13   213.5 1455.38   223.4 1459.66   233.3 1463.02   243.2 1465.79
   262.9  1470.2   282.7 1473.42   292.6 1474.85   302.5 1476.49   312.4 1478.44
   322.3 1480.78   332.2 1483.47   342.1 1486.35     352 1489.38   371.8  1495.9
#Mann= 3 , 0 , 0
       0      .1       0   183.7    .045       0   203.7      .1       0
Bank Sta=183.7,203.7
XS Rating Curve= 0 ,0
Exp/Cntr=0.3,0.1