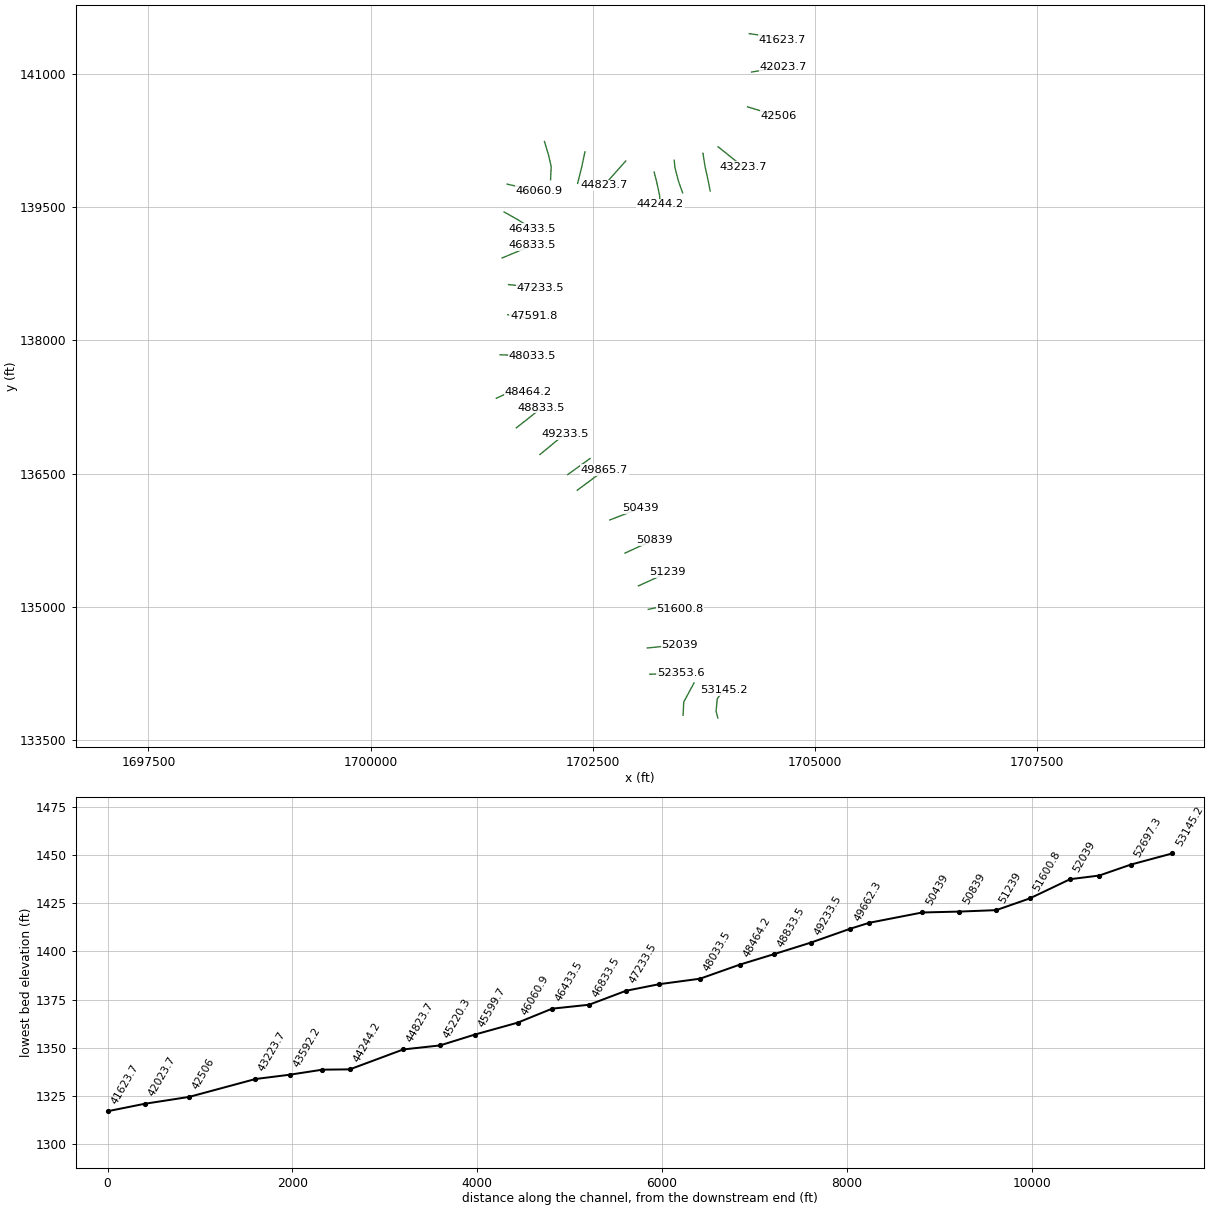
HEC-RAS study Panther Creek.prj: Panther Creek

--- Panther Creek.g01 (geometry) --- (continued)

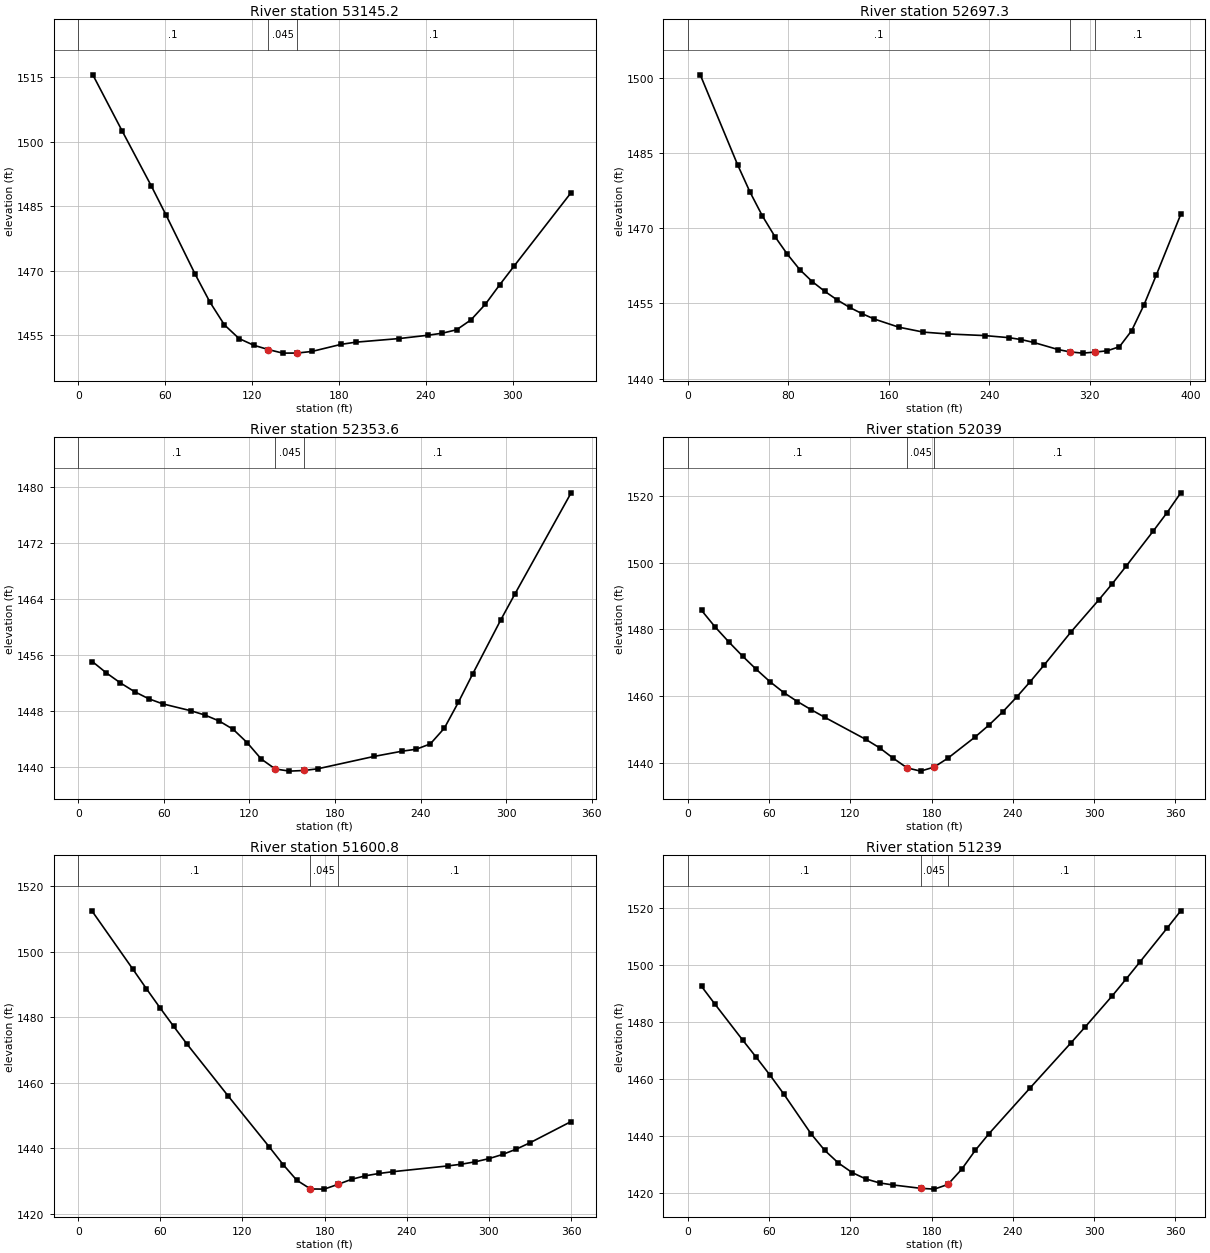
Type RM Length L Ch R = 1 ,53145.2 ,456.1,447.9,438.6
XS GIS Cut Line= 4
     1703908.207      133750.766     1703887.974         133829.
     1703901.463      133969.283     1703972.953      134063.704
#Sta/Elev= 24
    10.1 1515.51    30.3  1502.5    50.5 1489.68    60.6 1482.97    80.8 1469.16
    90.9 1462.74   100.9 1457.45     111 1454.27   121.1 1452.72   131.2 1451.71
   141.2 1450.88   151.2  1450.9   161.3 1451.27   181.5 1452.92   191.5 1453.42
   221.7 1454.27   241.5 1455.04   251.3 1455.51   261.2 1456.31   271.1 1458.61
     281 1462.23   290.8  1466.7   300.7 1471.04   340.2 1488.16
#Mann= 3 , 0 , 0
       0      .1       0   131.2    .045       0   151.2      .1       0
Bank Sta=131.2,151.2
XS Rating Curve= 0 ,0
Exp/Cntr=0.3,0.1

Type RM Length L Ch R = 1 ,52697.3 ,366.6,343.7,318
XS GIS Cut Line= 3
     1703517.035      133783.139      1703523.78      133931.514
     1703639.783      134145.985
#Sta/Elev= 30
     9.9 1500.58    39.6 1482.66    49.5  1477.2    59.4 1472.42    69.3 1468.34
    79.2 1464.82    89.1 1461.74      99 1459.36   108.9 1457.43   118.8 1455.72
   128.7 1454.22   138.6 1452.97   148.5 1451.88     168 1450.26   187.5 1449.28
     207 1448.91   236.3 1448.59   255.8 1448.17   265.6 1447.78   275.3 1447.22
   294.8  1445.8   304.3 1445.33   314.3 1445.09   324.3  1445.3   333.8 1445.55
   343.6 1446.37   353.3 1449.57   363.1  1454.7   372.9 1460.65   392.4 1472.76
#Mann= 3 , 0 , 0
       0      .1       0   304.3    .045       0   324.3      .1       0
Bank Sta=304.3,324.3
XS Rating Curve= 0 ,0
Exp/Cntr=0.3,0.1

Type RM Length L Ch R = 1 ,52353.6 ,312.2,314.5,320.5
XS GIS Cut Line= 2
     1703143.399      134244.452     1703488.709      134255.243
#Sta/Elev= 26
     9.9 1455.05    19.7 1453.43    29.6 1451.99    39.5 1450.74    49.4 1449.73
    59.2    1449      79 1448.01    88.8  1447.4    98.7 1446.56   108.6 1445.36
   118.4 1443.46   128.3 1441.11   138.1 1439.69   148.1 1439.38   158.1 1439.47
   167.8 1439.71   207.3 1441.48     227 1442.23   236.9 1442.51   246.8 1443.27
   256.6 1445.51   266.5 1449.23   276.4 1453.23   296.1 1460.97     306 1464.67
   345.5 1479.17
#Mann= 3 , 0 , 0
       0      .1       0   138.1    .045       0   158.1      .1       0
Bank Sta=138.1,158.1
XS Rating Curve= 0 ,0
Exp/Cntr=0.3,0.1

Type RM Length L Ch R = 1 ,52039   ,441.5,438.2,435
XS GIS Cut Line= 3
     1703114.029      134539.474     1703295.105      134557.791
     1703476.181      134576.107
#Sta/Elev= 30
    10.1 1485.72    20.2 1480.71    30.3 1476.23    40.4    1472    50.6    1468
    60.7  1464.3    70.8 1461.07    80.9 1458.37      91 1455.94   101.1 1453.64
   131.4 1447.02   141.6 1444.49   151.7 1441.36   161.9 1438.47   171.9  1437.5
   181.9 1438.72   192.1  1441.4   212.3 1447.79   222.4 1451.33   232.6  1455.3
   242.7 1459.66   252.8 1464.32   262.9 1469.22   283.1 1479.32   303.3 1488.77
   313.4 1493.69   323.6 1498.94   343.8 1509.56   353.9 1515.04     364 1520.96
#Mann= 3 , 0 , 0
       0      .1       0   161.9    .045       0   181.9      .1       0
Bank Sta=161.9,181.9
XS Rating Curve= 0 ,0
Exp/Cntr=0.3,0.1

Type RM Length L Ch R = 1 ,51600.8 ,351.5,361.8,372
XS GIS Cut Line= 3
     1703124.744      134974.327     1703241.866       134998.47
     1703481.965      134983.632
#Sta/Elev= 25
      10 1512.43    39.9 1494.65    49.8 1488.68    59.8 1482.81    69.8 1477.13
    79.7 1471.64   109.6 1455.89   139.6 1440.36   149.7 1434.98   159.7 1430.19
   169.7 1427.54   179.7 1427.48   189.7 1428.92   199.8 1430.49   209.8 1431.55
   219.8 1432.26   229.8  1432.8   269.9 1434.56     280 1435.09     290 1435.82
     300 1436.78     310 1438.06     320 1439.68   330.1 1441.64   360.1 1448.11
#Mann= 3 , 0 , 0
       0      .1       0   169.7    .045       0   189.7      .1       0
Bank Sta=169.7,189.7
XS Rating Curve= 0 ,0
Exp/Cntr=0.3,0.1

Type RM Length L Ch R = 1 ,51239   ,399.9,400,399.4
XS GIS Cut Line= 3
     1703013.901      135238.087     1703179.415      135313.779
     1703344.928      135389.471
#Sta/Elev= 27
    10.1 1492.43    20.2 1486.09    40.4 1473.68    50.6 1467.54    60.7 1461.33
    70.8 1454.76      91 1440.78   101.1 1434.99   111.2 1430.56   121.3 1427.23
   131.4 1424.99   141.6 1423.59   151.7 1422.87     172  1421.7     182 1421.42
     192 1423.05   202.2 1428.37   212.3 1435.03   222.4 1440.85   252.8 1456.89
   283.1 1472.74   293.2  1478.1   313.4 1489.11   323.6 1494.97   333.7 1500.89
   353.9 1512.82     364 1518.88
#Mann= 3 , 0 , 0
       0      .1       0     172    .045       0     192      .1       0
Bank Sta=172,192
XS Rating Curve= 0 ,0
Exp/Cntr=0.3,0.1

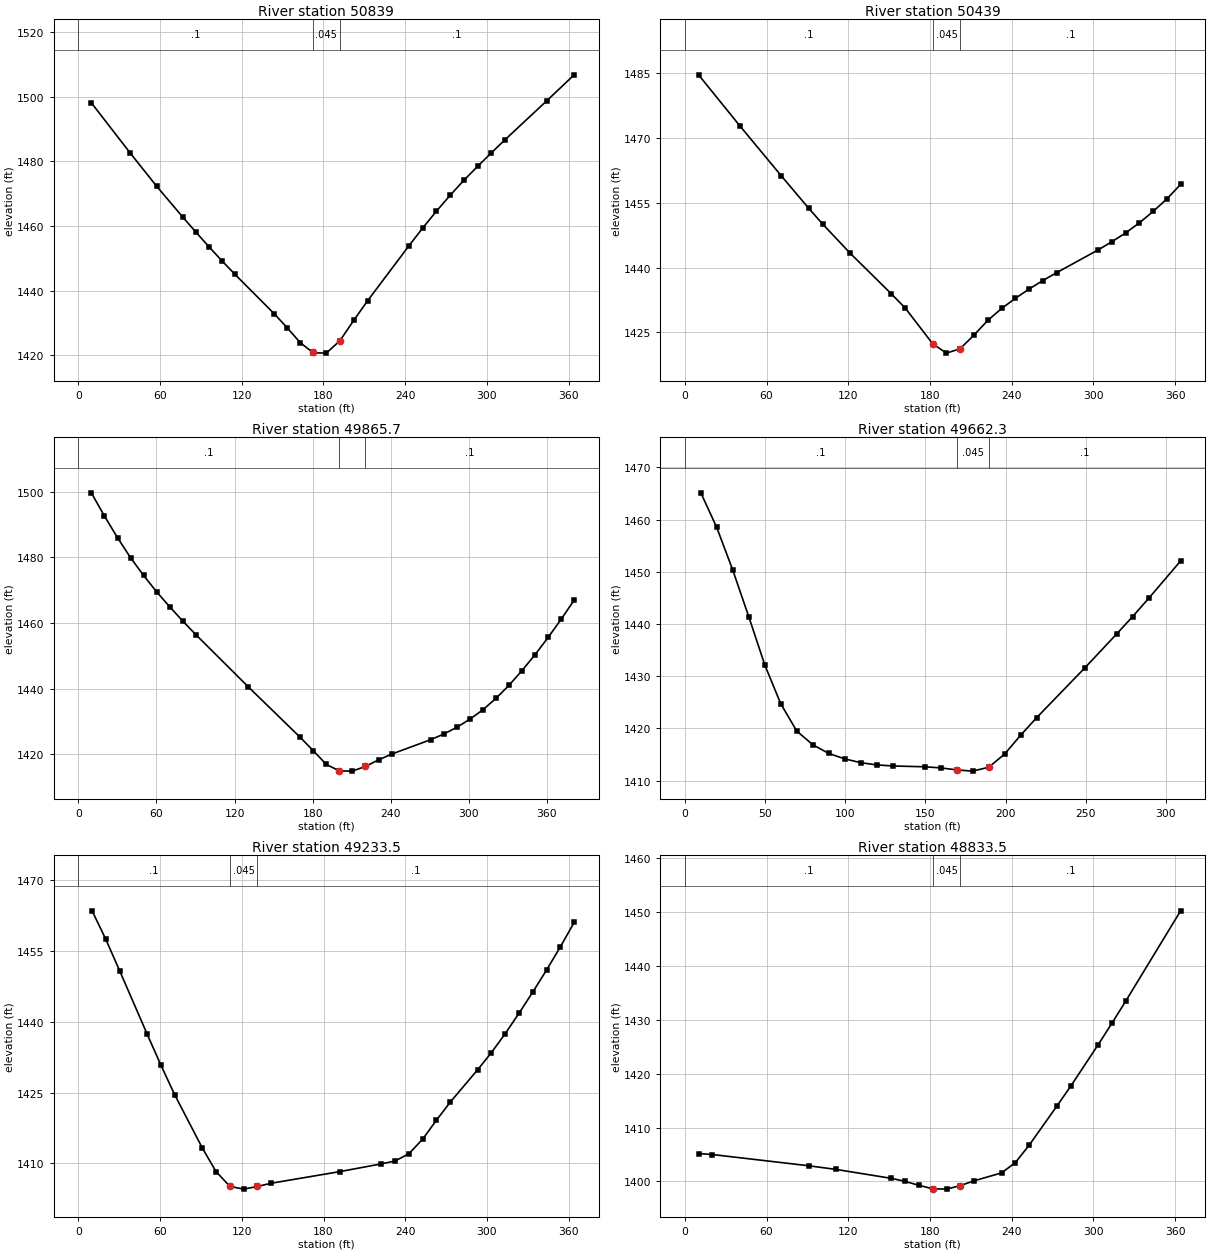
Type RM Length L Ch R = 1 ,50839   ,401.3,400,399.3
XS GIS Cut Line= 3
     1702863.472      135607.536      1703028.83      135683.824
     1703196.373      135754.862
#Sta/Elev= 27
     9.6 1498.14    38.3 1482.51    57.5 1472.34    76.7 1462.78    86.3 1458.15
    95.8 1453.66   105.4 1449.28     115 1445.06   143.8 1432.88   153.4 1428.51
   162.9 1423.93   172.1  1420.9   172.5 1420.77   182.1 1420.67   192.1 1424.53
   202.3 1430.84   212.4 1436.88   242.8 1453.91   252.9 1459.42     263 1464.63
   273.1 1469.56   283.2 1474.22   293.3 1478.53   303.4 1482.73   313.5  1486.8
   343.9 1498.76   364.1 1506.83
#Mann= 3 , 0 , 0
       0      .1       0   172.1    .045       0   192.1      .1       0
Bank Sta=172.1,192.1
XS Rating Curve= 0 ,0
Exp/Cntr=0.3,0.1

Type RM Length L Ch R = 1 ,50439   ,567.9,573.3,578.7
XS GIS Cut Line= 3
     1702691.547      135979.975     1702861.363      136045.447
     1703031.179      136110.919
#Sta/Elev= 25
    10.1 1484.59    40.4 1472.79    70.8 1461.24      91  1453.7   101.1  1450.1
   121.3 1443.35   151.7  1433.9   161.8 1430.64   182.1 1422.33   192.1 1420.21
   202.1 1421.23   212.3 1424.38   222.4 1427.77   232.6 1430.54   242.7 1432.89
   252.8 1435.05   262.9 1437.01     273 1438.83   303.3 1444.06   313.4 1445.96
   323.6 1448.01   333.7 1450.35   343.8 1452.98   353.9 1455.88     364 1459.25
#Mann= 3 , 0 , 0
       0      .1       0   182.1    .045       0   202.1      .1       0
Bank Sta=182.1,202.1
XS Rating Curve= 0 ,0
Exp/Cntr=0.3,0.1

Type RM Length L Ch R = 1 ,49865.7 ,203.6,203.4,203.1
XS GIS Cut Line= 2
     1702325.984      136314.966     1702632.177      136541.576
#Sta/Elev= 30
      10 1499.69      20 1492.65    30.1 1486.02    40.1 1479.92    50.1 1474.52
    60.1 1469.54    70.2 1464.95    80.2 1460.62    90.2 1456.49   130.3 1440.65
   170.4 1425.18   180.4 1421.12   190.5 1416.91   200.5 1414.93   210.5 1414.86
   220.5 1416.29   230.6 1418.27   240.6 1420.04   270.7 1424.45   280.7 1426.15
   290.7 1428.21   300.7 1430.66   310.8 1433.56   320.8 1437.03   330.8    1441
   340.8  1445.5   350.9 1450.38   360.9 1455.61   370.9 1461.14   380.9 1466.99
#Mann= 3 , 0 , 0
       0      .1       0   200.5    .045       0   220.5      .1       0
Bank Sta=200.5,220.5
XS Rating Curve= 0 ,0
Exp/Cntr=0.3,0.1

Type RM Length L Ch R = 1 ,49662.3 ,427.7,428.8,430
XS GIS Cut Line= 2
     1702218.075      136490.319     1702468.964      136671.067
#Sta/Elev= 26
      10 1465.13    19.9 1458.51    29.9 1450.34    39.9 1441.39    49.9 1432.14
    59.8 1424.74    69.8 1419.49    79.8 1416.87    89.8 1415.19    99.7 1414.16
   109.7 1413.43   119.7    1413   129.7  1412.8   149.6 1412.64   159.6 1412.43
   169.5 1412.05   179.5 1411.81   189.5 1412.55   199.5 1415.09   209.5 1418.71
   219.4 1422.05   249.4 1431.57   269.3 1438.09   279.3 1441.43   289.3 1444.92
   309.2 1452.08
#Mann= 3 , 0 , 0
       0      .1       0   169.5    .045       0   189.5      .1       0
Bank Sta=169.5,189.5
XS Rating Curve= 0 ,0
Exp/Cntr=0.3,0.1

Type RM Length L Ch R = 1 ,49233.5 ,400.4,400,399.8
XS GIS Cut Line= 3
     1701906.216      136716.797      1702046.81       136832.37
     1702187.405      136947.944
#Sta/Elev= 27
    10.1 1463.54    20.2 1457.48    30.3 1450.86    50.6 1437.36    60.7 1430.78
    70.8 1424.53      91 1413.29   101.1 1408.27   111.3 1405.14   121.3 1404.56
   131.3 1405.12   141.6 1405.81   192.1 1408.28   222.4 1409.91   232.6 1410.53
   242.7 1412.07   252.8 1415.16   262.9 1419.17     273 1422.98   293.2 1429.88
   303.3 1433.51   313.4 1437.52   323.6 1441.88   333.7 1446.36   343.8 1451.02
   353.9 1455.92     364 1461.08
#Mann= 3 , 0 , 0
       0      .1       0   111.3    .045       0   131.3      .1       0
Bank Sta=111.3,131.3
XS Rating Curve= 0 ,0
Exp/Cntr=0.3,0.1

Type RM Length L Ch R = 1 ,48833.5 ,381.6,369.4,357
XS GIS Cut Line= 3
      1701640.47      137016.886     1701783.439      137129.607
     1701925.298      137243.571
#Sta/Elev= 20
    10.1 1405.16    20.2 1404.98      91 1402.89   111.3  1402.2   151.7 1400.55
   161.8 1399.99   171.9 1399.25   182.2 1398.61   192.2 1398.55   202.2  1399.2
   212.4  1400.1   232.6 1401.57   242.7 1403.49   252.8 1406.71     273 1413.93
   283.2 1417.63   303.4 1425.36   313.5 1429.35   323.6 1433.44     364 1450.26
#Mann= 3 , 0 , 0
       0      .1       0   182.2    .045       0   202.2      .1       0
Bank Sta=182.2,202.2
XS Rating Curve= 0 ,0
Exp/Cntr=0.3,0.1

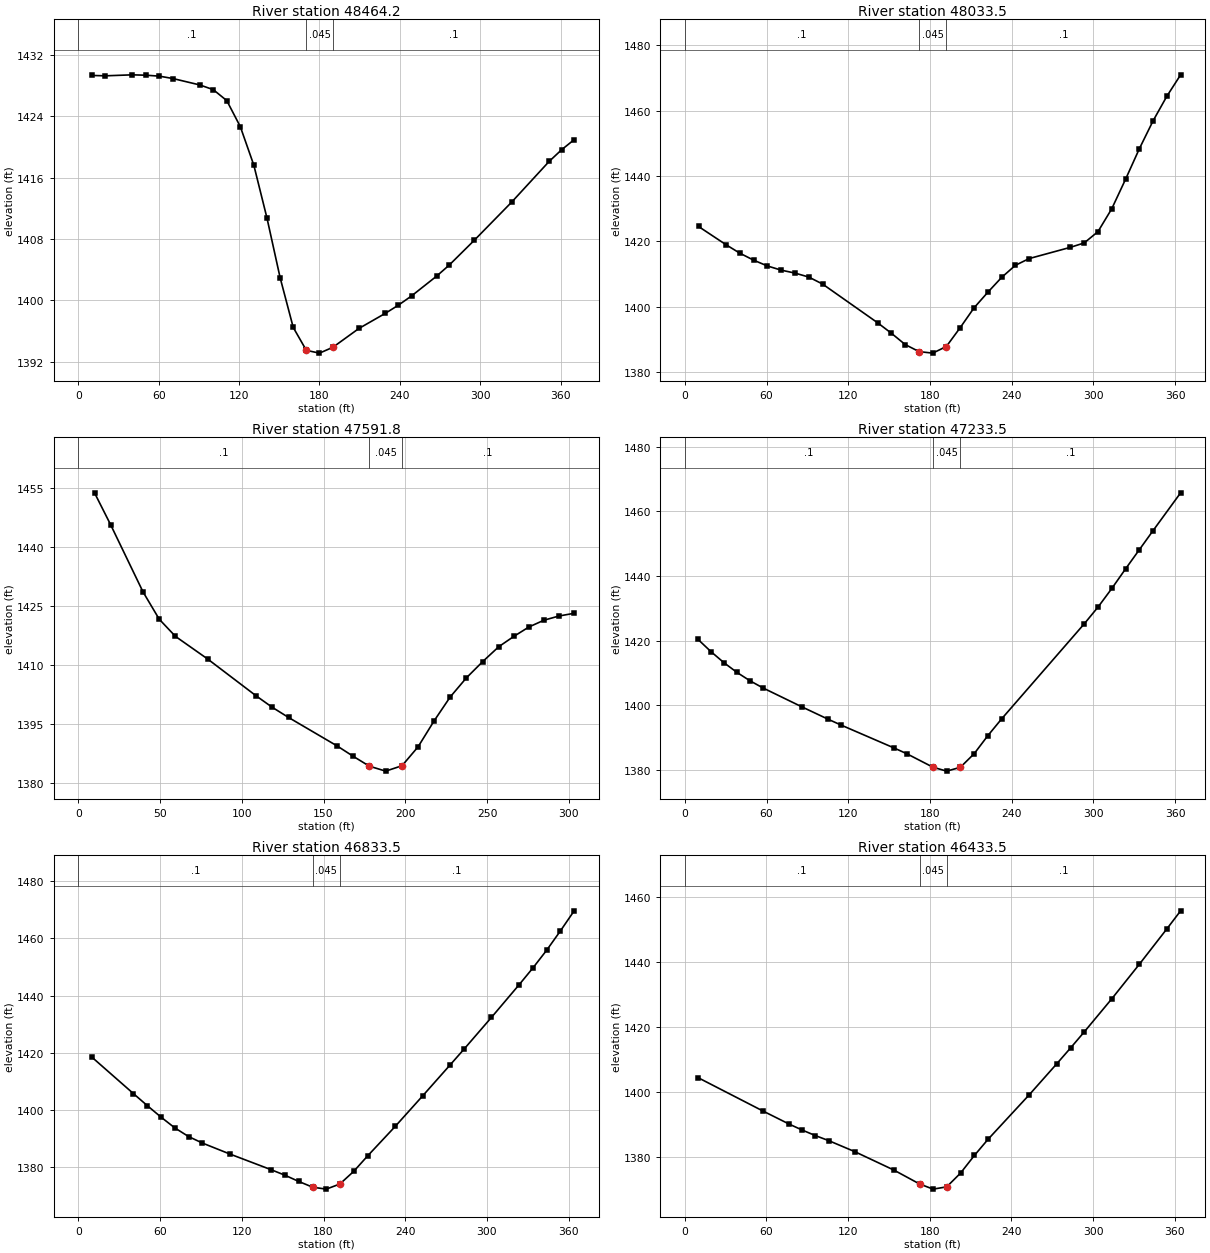
Type RM Length L Ch R = 1 ,48464.2 ,433.5,430.6,427.8
XS GIS Cut Line= 4
     1701415.498      137349.548     1701534.198      137404.852
      1701651.55      137414.294     1701772.948      137415.643
#Sta/Elev= 29
    10.1 1429.31    20.1 1429.26    40.3 1429.39    50.4 1429.34    60.4 1429.22
    70.5 1428.91    90.7 1428.07   100.7 1427.46   110.8 1426.03   120.9 1422.64
     131 1417.61   140.8 1410.73   150.6 1402.97   160.4 1396.47     170 1393.54
   170.2 1393.48     180 1393.12     190 1393.88   209.4 1396.33   229.1  1398.3
   238.9 1399.37   248.7 1400.57   267.4 1403.15   276.7 1404.57   295.4  1407.8
   323.4 1412.79   351.4  1418.1   360.7 1419.62   370.1 1420.94
#Mann= 3 , 0 , 0
       0      .1       0     170    .045       0     190      .1       0
Bank Sta=170,190
XS Rating Curve= 0 ,0
Exp/Cntr=0.3,0.1

Type RM Length L Ch R = 1 ,48033.5 ,444.1,441.7,439.3
XS GIS Cut Line= 3
     1701457.225      137838.987     1701639.109      137832.481
     1701820.993      137825.976
#Sta/Elev= 30
    10.1 1424.54    30.3 1418.96    40.4 1416.38    50.6 1414.23    60.7 1412.46
    70.8 1411.19    80.9 1410.29      91 1409.08   101.1 1406.95   141.6 1395.08
   151.7 1391.88   161.8 1388.43     172 1386.27     182 1385.81     192 1387.83
   202.2 1393.61   212.3 1399.64   222.4  1404.4   232.6 1408.97   242.7 1412.67
   252.8 1414.73   283.1 1418.17   293.2 1419.51   303.3 1422.96   313.4 1429.93
   323.6 1439.01   333.7 1448.33   343.8 1456.88   353.9 1464.39     364 1470.93
#Mann= 3 , 0 , 0
       0      .1       0     172    .045       0     192      .1       0
Bank Sta=172,192
XS Rating Curve= 0 ,0
Exp/Cntr=0.3,0.1

Type RM Length L Ch R = 1 ,47591.8 ,357.1,358.3,358.7
XS GIS Cut Line= 3
     1701543.147      138289.334     1701797.228      138249.244
     1701836.345      138273.524
#Sta/Elev= 25
     9.9 1453.66    19.8 1445.52    39.6 1428.47    49.5 1421.55    59.4  1417.2
    79.1 1411.45   108.8 1402.08   118.7 1399.16   128.6  1396.6   158.3 1389.37
   168.2 1386.72     178 1384.23     188 1382.97     198 1384.34   207.8 1389.13
   217.7 1395.78   227.5 1401.82   237.4 1406.67   247.3 1410.77   257.2 1414.58
   266.4 1417.19   275.6 1419.58   284.8  1421.3   294.1 1422.38   303.3 1423.06
#Mann= 3 , 0 , 0
       0      .1       0     178    .045       0     198      .1       0
Bank Sta=178,198
XS Rating Curve= 0 ,0
Exp/Cntr=0.3,0.1

Type RM Length L Ch R = 1 ,47233.5 ,390.1,400,410.6
XS GIS Cut Line= 3
     1701552.533      138628.593     1701733.866      138611.355
     1701914.265      138587.467
#Sta/Elev= 24
     9.6 1420.38    19.2 1416.56    28.8 1413.11    38.3 1410.12    47.9 1407.52
    57.5 1405.29    86.3 1399.39   105.5 1395.57     115 1393.77   153.4 1386.77
     163 1384.94   182.3 1380.75   192.3 1379.55   202.3 1380.72   212.5 1384.95
   222.6 1390.57   232.7 1395.75   293.4  1425.2   303.5 1430.38   313.6 1436.13
   323.7  1442.2   333.8 1448.13   343.9 1454.05   364.1 1465.73
#Mann= 3 , 0 , 0
       0      .1       0   182.3    .045       0   202.3      .1       0
Bank Sta=182.3,202.3
XS Rating Curve= 0 ,0
Exp/Cntr=0.3,0.1

Type RM Length L Ch R = 1 ,46833.5 ,418.8,400,379.9
XS GIS Cut Line= 3
      1701481.28      138928.489     1701649.145      138998.812
      1701817.01      139069.134
#Sta/Elev= 26
    10.1  1418.4    40.4 1405.73    50.6 1401.52    60.7 1397.49    70.8 1393.73
    80.9  1390.7      91 1388.43   111.2 1384.59   141.6 1379.08   151.7 1377.16
   161.8 1374.99     172 1372.98     182  1372.3     192 1374.09   202.2 1378.53
   212.3 1383.88   232.6 1394.22   252.8 1404.93     273 1415.78   283.1 1421.24
   303.3 1432.38   323.6  1443.8   333.7 1449.66   343.8 1455.86   353.9 1462.62
     364 1469.65
#Mann= 3 , 0 , 0
       0      .1       0     172    .045       0     192      .1       0
Bank Sta=172,192
XS Rating Curve= 0 ,0
Exp/Cntr=0.3,0.1

Type RM Length L Ch R = 1 ,46433.5 ,366.6,372.7,380.5
XS GIS Cut Line= 3
     1701502.802      139445.712     1701661.936       139356.39
     1701814.309      139257.017
#Sta/Elev= 22
     9.6 1404.49    57.6 1394.19    76.8 1390.19    86.4 1388.36      96 1386.68
   105.7 1385.15   124.9 1381.76   153.7  1376.1   172.5 1371.85   182.5 1370.26
   192.5 1370.96   202.7  1375.2   212.8 1380.58   222.9 1385.56   253.2 1399.23
   273.4 1408.73   283.6 1413.61   293.7 1418.56   313.9  1428.7   334.1 1439.27
   354.3 1450.11   364.4 1455.64
#Mann= 3 , 0 , 0
       0      .1       0   172.5    .045       0   192.5      .1       0
Bank Sta=172.5,192.5
XS Rating Curve= 0 ,0
Exp/Cntr=0.3,0.1

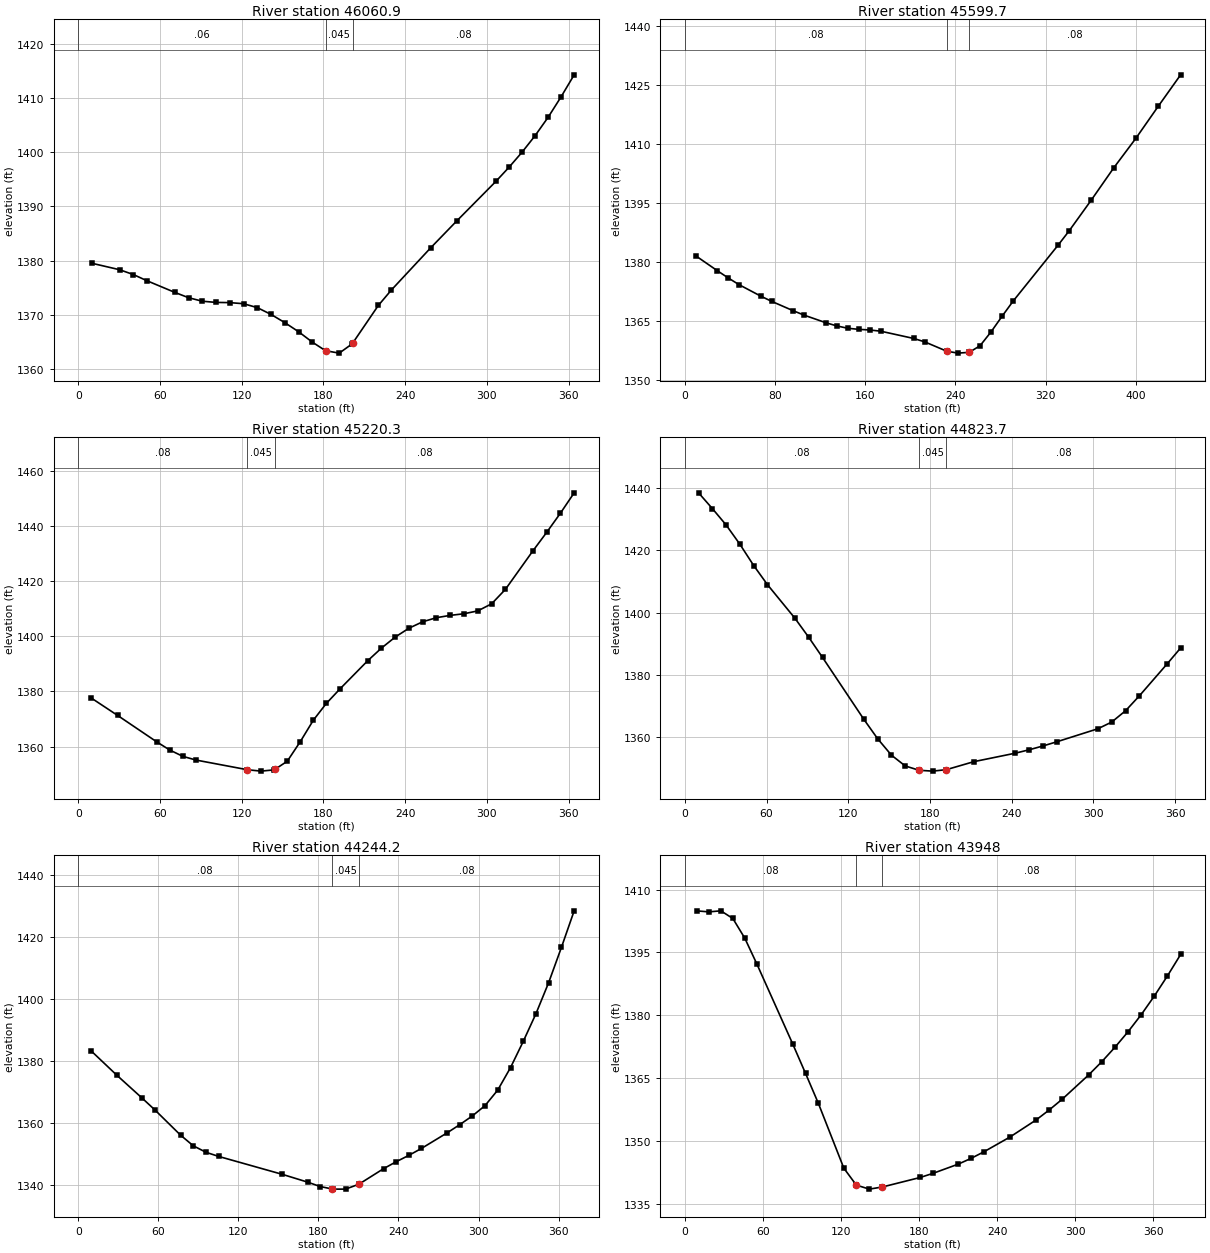
Type RM Length L Ch R = 1 ,46060.9 ,484.2,461.2,437.2
XS GIS Cut Line= 3
     1701536.553      139759.264     1701714.018      139719.015
     1701892.913      139684.683
#Sta/Elev= 30
    10.1 1379.53    30.3 1378.35    40.4 1377.46    50.5 1376.31    70.8 1374.18
    80.9  1373.2      91 1372.55   101.1 1372.33   111.2 1372.29   121.3 1372.09
   131.4 1371.37   141.5 1370.12   151.6 1368.61   161.8 1366.92   171.9    1365
   181.6 1363.43   191.6 1362.99   201.1  1364.7   201.6 1364.88   220.3 1371.77
   229.9 1374.62   258.7 1382.37   277.8 1387.31   306.6 1394.61   316.2  1397.2
   325.8 1399.98   335.4 1403.03     345 1406.43   354.5 1410.19   364.1 1414.24
#Mann= 3 , 0 , 0
       0     .06       0   181.6    .045       0   201.6     .08       0
Bank Sta=181.6,201.6
XS Rating Curve= 0 ,0
Exp/Cntr=0.3,0.1

Type RM Length L Ch R = 1 ,45599.7 ,388.2,379.3,371
XS GIS Cut Line= 4
     1701956.756      140238.756     1702001.402      140091.288
     1702032.437      139957.755     1702025.692      139809.379
#Sta/Elev= 30
     9.6 1381.61    28.9 1377.79    38.5 1375.96    48.1 1374.25    67.4 1371.33
      77 1370.01    96.3  1367.6   105.9 1366.49   125.2 1364.56   134.8 1363.76
   144.4 1363.17   154.1 1362.89   163.9 1362.73   173.7 1362.42     203 1360.57
   212.8  1359.7   232.2 1357.34   242.2 1356.84   252.2 1357.04   261.8 1358.71
   271.6 1362.25   281.4 1366.23   291.2 1370.08   330.8 1384.21   340.7 1387.88
   360.5 1395.77   380.3 1403.92   400.1  1411.5   419.9 1419.63   439.7 1427.61
#Mann= 3 , 0 , 0
       0     .08       0   232.2    .045       0   252.2     .08       0
Bank Sta=232.2,252.2
XS Rating Curve= 0 ,0
Exp/Cntr=0.3,0.1

Type RM Length L Ch R = 1 ,45220.3 ,407,396.6,386.2
XS GIS Cut Line= 3
     1702412.279      140122.751     1702374.344      139944.609
     1702330.208      139768.066
#Sta/Elev= 30
     9.6 1377.61    28.8 1371.35    57.5 1361.79    67.1 1358.82    76.7 1356.53
    86.3 1355.19   124.2 1351.67   134.2 1351.17   143.8 1351.63   144.2 1351.76
   153.4 1354.74     163 1361.85   172.6 1369.63   182.1 1375.68   192.2 1380.97
   212.5 1391.14   222.6 1395.72   232.7 1399.71   242.8 1402.92   252.9 1405.25
     263 1406.73   273.1 1407.56   283.2 1408.15   293.3 1409.18   303.5 1411.75
   313.6 1416.97   333.8 1430.91   343.9  1437.6     354 1444.55   364.1 1451.93
#Mann= 3 , 0 , 0
       0     .08       0   124.2    .045       0   144.2     .08       0
Bank Sta=124.2,144.2
XS Rating Curve= 0 ,0
Exp/Cntr=0.3,0.1

Type RM Length L Ch R = 1 ,44823.7 ,560,579.4,598.9
XS GIS Cut Line= 3
     1702871.595      140019.635     1702750.548      139883.724
     1702629.502      139747.813
#Sta/Elev= 27
    10.1 1438.49    20.2 1433.45    30.3 1428.18    40.4    1422    50.6 1415.12
    60.7 1408.98    80.9 1398.17      91 1392.07   101.1 1385.62   131.4 1365.76
   141.6 1359.48   151.7 1354.22   161.8 1350.76     172 1349.36     182 1349.09
     192 1349.56   212.3 1352.14   242.7 1354.86   252.8 1355.95   262.9 1357.17
     273  1358.5   303.3 1362.71   313.4 1364.85   323.6  1368.5   333.7 1373.27
   353.9 1383.44     364 1388.65
#Mann= 3 , 0 , 0
       0     .08       0     172    .045       0     192     .08       0
Bank Sta=172,192
XS Rating Curve= 0 ,0
Exp/Cntr=0.3,0.1

Type RM Length L Ch R = 1 ,44244.2 ,295.5,296.2,297
XS GIS Cut Line= 4
     1703190.778       139895.37     1703219.441      139784.088
     1703251.477      139635.713     1703261.593      139531.175
#Sta/Elev= 30
     9.6 1383.35    28.7 1375.56    47.9 1368.08    57.5 1364.26    76.6 1356.18
    86.2 1352.72    95.8 1350.62   105.3 1349.29   152.9 1343.52   171.8 1341.02
   181.3 1339.59   190.3  1338.8   190.8 1338.75   200.3 1338.75   210.3 1340.33
   228.8 1345.34   238.2 1347.57   247.7 1349.63   257.2 1351.87   276.3 1356.86
   285.8 1359.51   295.4 1362.37   304.9 1365.69   314.4  1370.7     324 1377.95
   333.5 1386.38   343.1 1395.38   352.6 1405.39   362.2 1416.79   371.7 1428.53
#Mann= 3 , 0 , 0
       0     .08       0   190.3    .045       0   210.3     .08       0
Bank Sta=190.3,210.3
XS Rating Curve= 0 ,0
Exp/Cntr=0.3,0.1

Type RM Length L Ch R = 1 ,43948   ,355.2,355.8,355.5
XS GIS Cut Line= 4
     1703416.713      140028.571     1703425.144      139945.952
     1703463.924      139794.205     1703511.134      139661.004
#Sta/Elev= 30
     9.2 1404.92    18.5 1404.68    27.7 1404.93    36.9 1403.11    46.1 1398.41
    55.4 1392.24      83 1373.14    92.8 1366.16   102.6 1359.06   122.2 1343.58
   131.8 1339.54   141.8 1338.58   151.8 1339.09   180.9 1341.36   190.7 1342.34
   210.3 1344.56   220.1 1345.93   229.9 1347.49   249.8 1350.99     270 1355.08
     280 1357.45   290.1 1360.04   310.3  1365.8   320.4 1368.95   330.5 1372.39
   340.6  1376.1   350.7 1380.16   360.8 1384.62   370.9 1389.43     381 1394.52
#Mann= 3 , 0 , 0
       0     .08       0   131.8    .045       0   151.8     .08       0
Bank Sta=131.8,151.8
XS Rating Curve= 0 ,0
Exp/Cntr=0.3,0.1

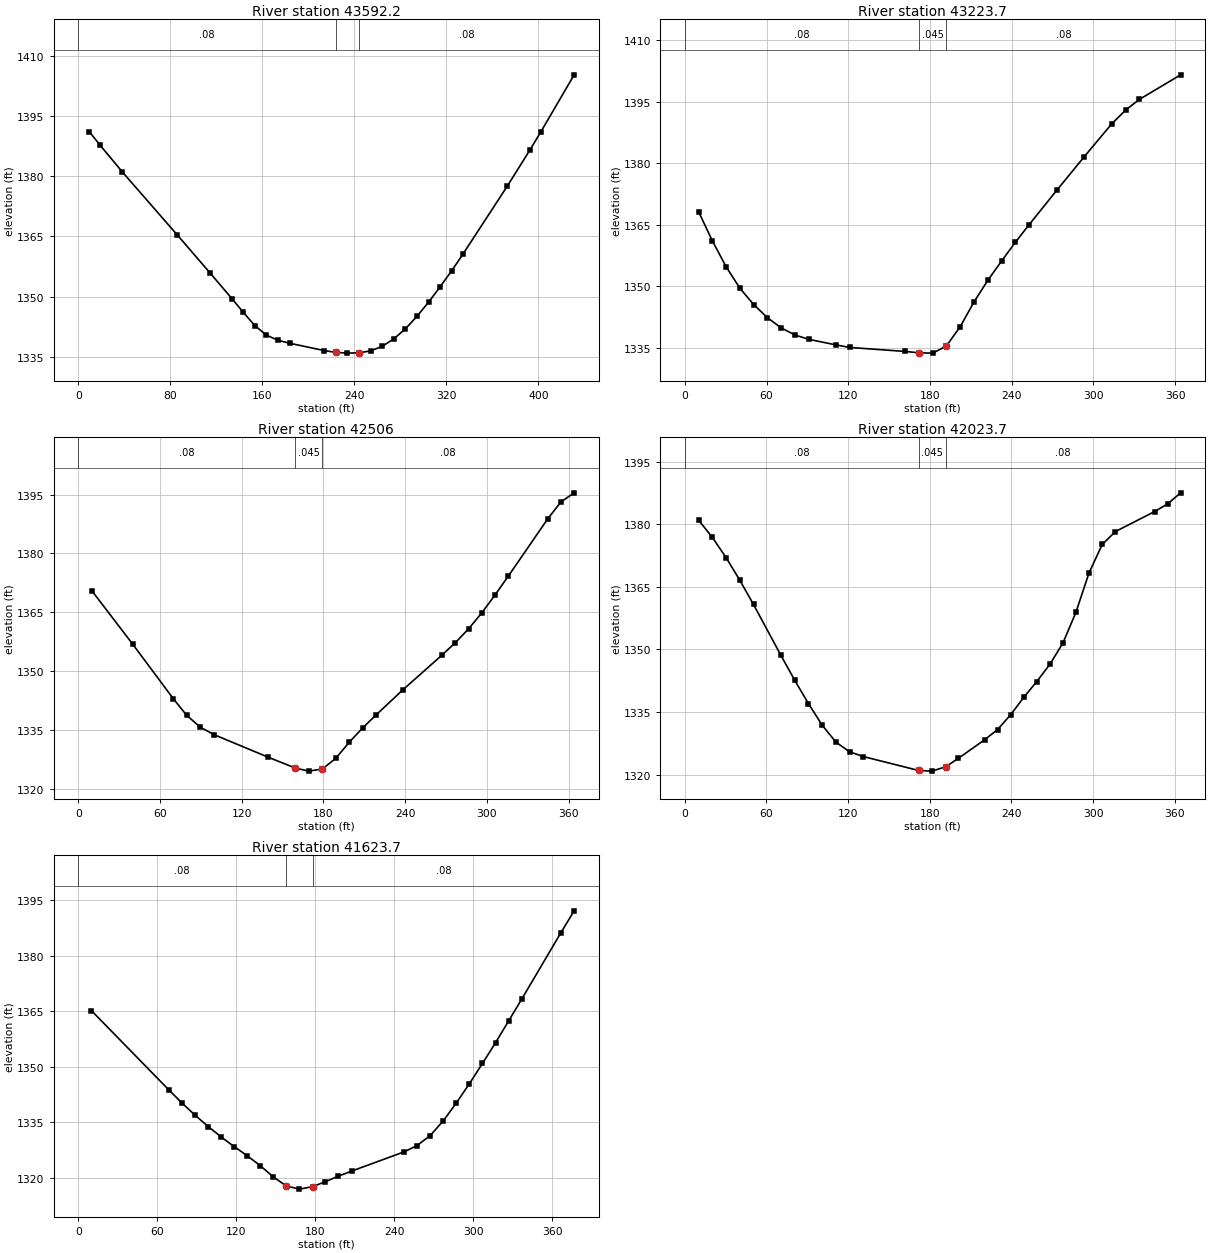
Type RM Length L Ch R = 1 ,43592.2 ,355.8,368.5,382.1
XS GIS Cut Line= 4
     1703740.442      140106.131     1703762.361      139964.499
     1703801.141       139787.46     1703821.374      139682.923
#Sta/Elev= 28
     9.6 1391.07    19.1 1387.66    38.2 1381.09      86 1365.38   114.7 1355.85
   133.8 1349.42   143.3 1346.14   153.4 1342.81   163.5 1340.43   173.5 1339.16
   183.6 1338.42   213.8 1336.58   223.9 1336.14   233.9 1335.95   243.9 1336.03
   254.1  1336.5   264.1 1337.63   274.2 1339.49   284.3    1342   294.3 1345.09
   304.4 1348.63   314.5 1352.47   324.6  1356.5   334.2 1360.54     373 1377.59
   392.3 1386.43     402 1391.03     431 1405.25
#Mann= 3 , 0 , 0
       0     .08       0   223.9    .045       0   243.9     .08       0
Bank Sta=223.9,243.9
XS Rating Curve= 0 ,0
Exp/Cntr=0.3,0.1

Type RM Length L Ch R = 1 ,43223.7 ,710,717.7,725.3
XS GIS Cut Line= 3
     1703911.105      140179.194     1704053.027      140065.256
      1704194.95      139951.318
#Sta/Elev= 27
    10.1 1368.25    20.2 1361.14    30.3 1354.83    40.4 1349.58    50.6 1345.57
    60.7 1342.36    70.8 1339.88    80.9 1338.15      91  1337.1   111.2 1335.72
   121.3 1335.11   161.8 1334.14     172  1333.8     182 1333.73     192 1335.45
   202.2 1340.18   212.3 1346.22   222.4 1351.46   232.6 1356.22   242.7 1360.78
   252.8 1365.08     273 1373.42   293.2 1381.63   313.4 1389.65   323.6 1393.01
   333.7 1395.62     364 1401.62
#Mann= 3 , 0 , 0
       0     .08       0     172    .045       0     192     .08       0
Bank Sta=172,192
XS Rating Curve= 0 ,0
Exp/Cntr=0.3,0.1

Type RM Length L Ch R = 1 ,42506   ,473.1,482.3,491
XS GIS Cut Line= 3
     1704241.782      140628.621     1704441.854      140568.118
     1704592.458      140531.041
#Sta/Elev= 24
      10 1370.44    39.8 1356.89    69.7 1342.94    79.6 1338.67    89.6 1335.64
    99.5 1333.77   139.3 1328.01   159.2 1325.24   169.2 1324.44   179.2 1324.99
   189.1 1327.72   199.1 1331.88     209 1335.54   218.7 1338.79   238.1 1345.12
   267.2  1354.1   276.9 1357.24   286.6 1360.76   296.3 1364.85     306  1369.4
   315.7 1374.18   344.7 1388.83   354.4 1393.13   364.1 1395.46
#Mann= 3 , 0 , 0
       0     .08       0   159.2    .045       0   179.2     .08       0
Bank Sta=159.2,179.2
XS Rating Curve= 0 ,0
Exp/Cntr=0.3,0.1

Type RM Length L Ch R = 1 ,42023.7 ,406.7,400,392.3
XS GIS Cut Line= 3
     1704287.638      141020.577     1704467.038      141050.196
     1704647.941      141074.888
#Sta/Elev= 30
    10.1 1380.99    20.2 1376.88    30.3 1372.03    40.4 1366.61    50.5 1360.78
    70.7 1348.56    80.8 1342.61    90.9 1337.02     101 1331.85   111.1  1327.8
   121.2 1325.48   131.3 1324.34   171.8 1321.02   181.8 1320.86   191.8 1321.92
     201 1323.91   220.3 1328.36   229.9 1330.83   239.5 1334.37   249.1 1338.53
   258.7 1342.33   268.3 1346.44   277.9 1351.54   287.5 1358.95   297.1 1368.37
   306.8 1375.16   316.4 1378.24   345.2 1383.03   354.8 1384.87   364.4 1387.53
#Mann= 3 , 0 , 0
       0     .08       0   171.8    .045       0   191.8     .08       0
Bank Sta=171.8,191.8
XS Rating Curve= 0 ,0
Exp/Cntr=0.3,0.1

Type RM Length L Ch R = 1 ,41623.7 ,382.2,382.2,383.8
XS GIS Cut Line= 3
     1704262.245      141452.706     1704457.708      141423.487
     1704632.188      141382.804
#Sta/Elev= 28
     9.9 1365.23    69.2 1343.64    79.1 1340.15    88.9 1336.91    98.8 1333.88
   108.7 1331.04   118.6 1328.45   128.5 1325.97   138.3 1323.32   148.2  1320.3
     158 1317.85     168    1317     178 1317.66   187.8 1319.02   197.6  1320.5
   207.6 1321.86   247.4 1327.04   257.4 1328.76   267.3 1331.44   277.3 1335.42
   287.2 1340.24   297.2 1345.48   307.1 1350.94   317.1 1356.57     327 1362.42
     337 1368.34   366.8  1386.3   376.8 1392.16
#Mann= 3 , 0 , 0
       0     .08       0     158    .045       0     178     .08       0
Bank Sta=158,178
XS Rating Curve= 0 ,0
Exp/Cntr=0.3,0.1