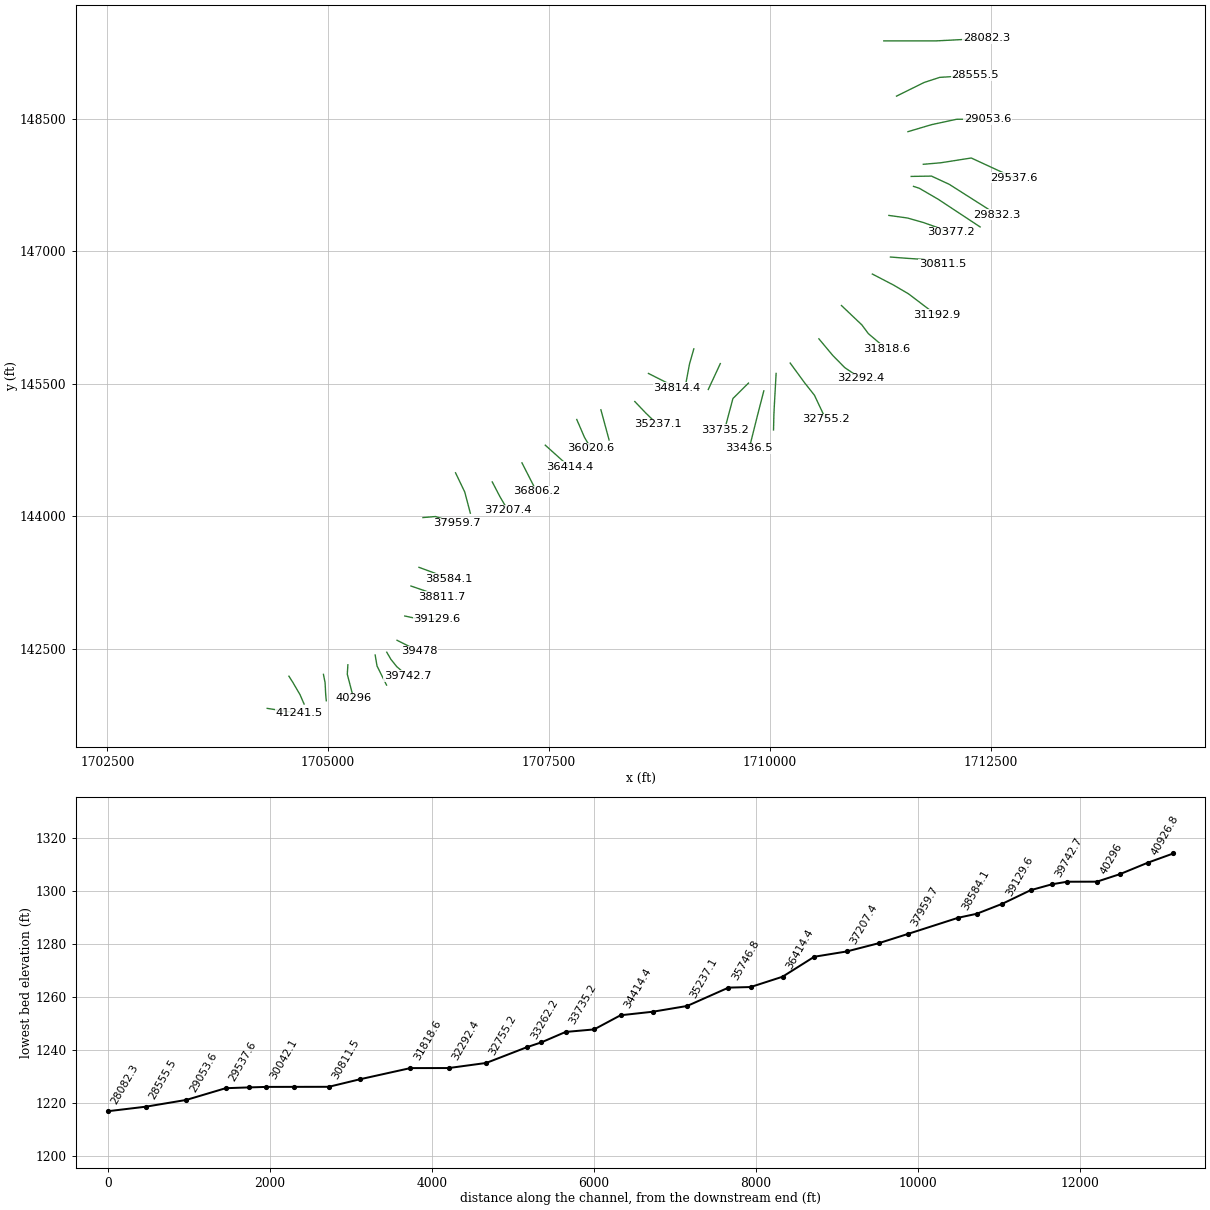
HEC-RAS study Panther Creek.prj: Panther Creek

--- Panther Creek.g01 (geometry) --- (continued)

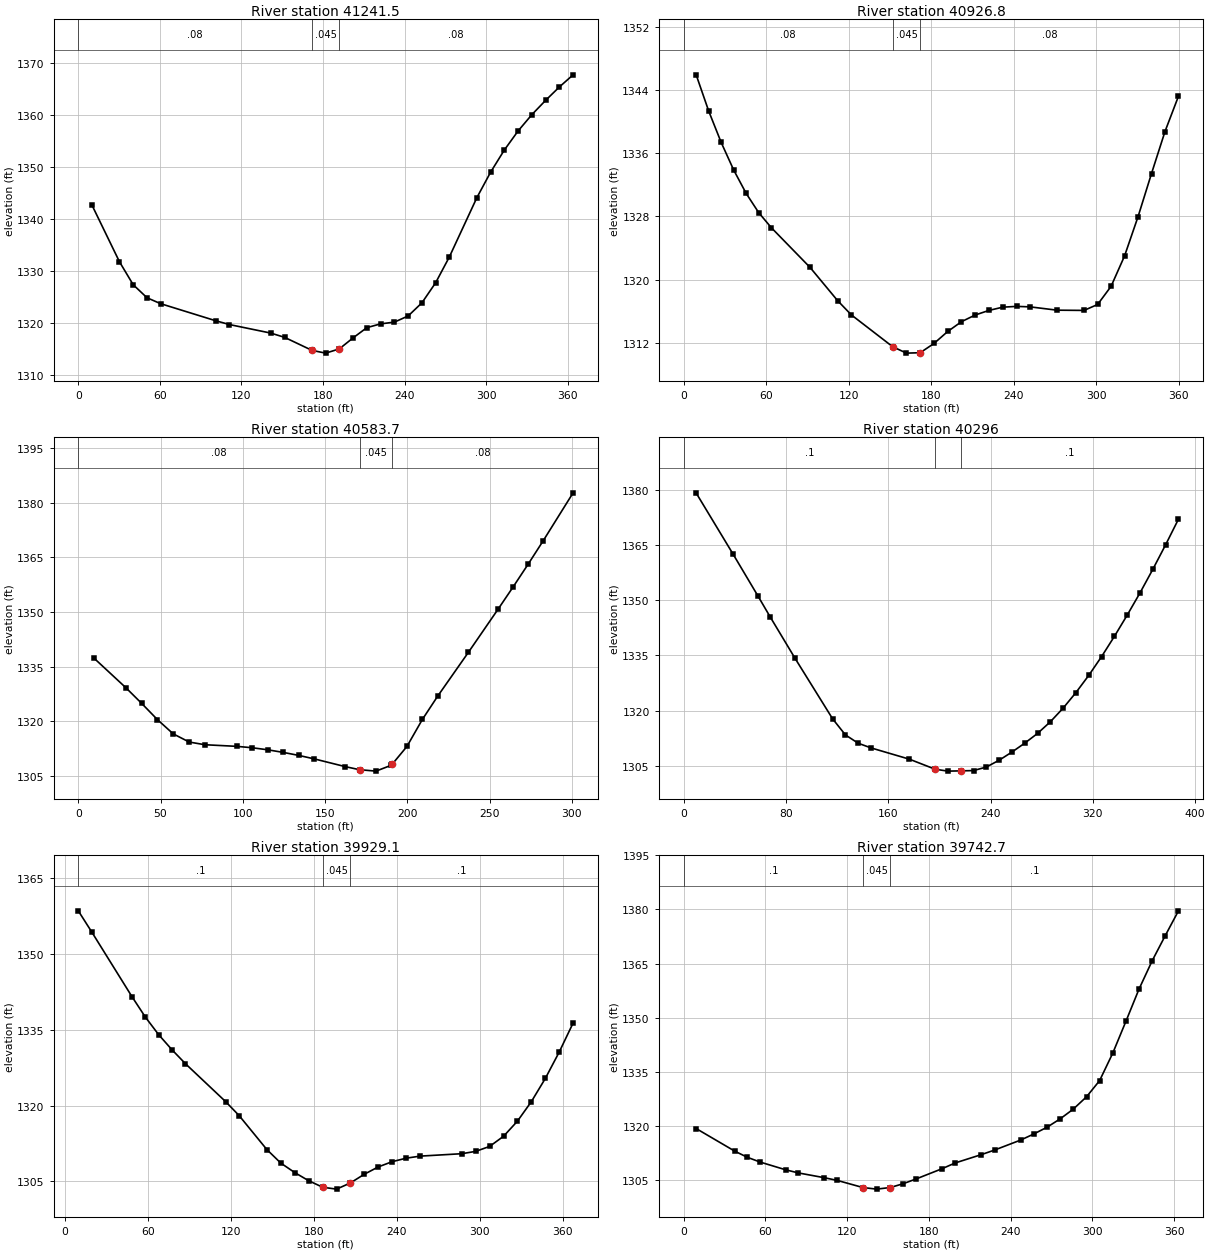
Type RM Length L Ch R = 1 ,41241.5 ,332.5,314.7,296.8
XS GIS Cut Line= 3
     1704310.584      141827.328     1704490.357      141798.942
      1704670.13      141770.555
#Sta/Elev= 28
    10.1 1342.59    30.3 1331.72    40.4 1327.31    50.6  1324.8    60.7 1323.66
   101.1 1320.39   111.2 1319.66   141.6 1318.02   151.7 1317.21     172 1314.69
     182 1314.17     192 1314.98   202.2 1317.11   212.3 1319.07   222.4 1319.79
   232.6 1320.13   242.7 1321.32   252.8 1323.84   262.9  1327.7     273 1332.67
   293.2 1344.04   303.3 1348.93   313.4 1353.19   323.6 1356.88   333.7    1360
   343.8 1362.74   353.9 1365.31     364 1367.64
#Mann= 3 , 0 , 0
       0     .08       0     172    .045       0     192     .08       0
Bank Sta=172,192
XS Rating Curve= 0 ,0
Exp/Cntr=0.3,0.1

Type RM Length L Ch R = 1 ,40926.8 ,352.8,343.1,333.4
XS GIS Cut Line= 4
     1704556.508      142191.819     1704600.346       142122.69
     1704681.278      141984.431     1704728.488      141876.521
#Sta/Elev= 30
     9.1 1345.94    18.2 1341.36    27.3 1337.37    36.4 1333.88    45.5 1330.91
    54.6 1328.48    63.7 1326.59    91.9 1321.55   111.9 1317.35   121.9 1315.54
     152  1311.5     162 1310.69     172 1310.74     182 1311.91     192 1313.43
     202 1314.67     212 1315.52     222  1316.1     232 1316.51   242.1 1316.61
   251.9 1316.55   271.5 1316.13   291.1  1316.1     301 1316.85   310.8 1319.15
   320.6    1323   330.4 1327.97   340.2 1333.44     350 1338.76   359.8 1343.23
#Mann= 3 , 0 , 0
       0     .08       0     152    .045       0     172     .08       0
Bank Sta=152,172
XS Rating Curve= 0 ,0
Exp/Cntr=0.3,0.1

Type RM Length L Ch R = 1 ,40583.7 ,283.4,287.6,291.9
XS GIS Cut Line= 4
      1704947.68      142212.052     1704966.227      142117.631
     1704972.971      141986.117     1704979.715      141913.615
#Sta/Elev= 27
     9.6 1337.35    28.9 1329.27    38.5 1324.97    48.1 1320.51    57.7  1316.6
    67.4 1314.36      77 1313.62    96.2 1313.18   105.6  1312.8     115 1312.24
   124.4 1311.53   133.9  1310.7   143.3 1309.75   162.1 1307.63   170.9 1306.77
   180.9 1306.38   190.3 1308.01   190.9 1308.34   199.7 1313.14   209.1 1320.56
   218.5 1327.01     237 1338.93   255.2 1350.87   264.3 1356.95   273.4 1363.17
   282.5 1369.56   300.7 1382.73
#Mann= 3 , 0 , 0
       0     .08       0   170.9    .045       0   190.9     .08       0
Bank Sta=170.9,190.9
XS Rating Curve= 0 ,0
Exp/Cntr=0.3,0.1

Type RM Length L Ch R = 1 ,40296   ,362.8,366.9,371.1
XS GIS Cut Line= 3
     1705224.198      142319.962     1705217.453      142213.738
     1705288.269      141942.278
#Sta/Elev= 30
     9.7  1379.3    38.7 1362.58    58.1 1351.21    67.7 1345.49    87.1 1334.24
   116.5 1317.75   126.5 1313.37   136.5  1311.1   146.5 1309.83   176.6 1306.75
   196.6 1304.03   206.6  1303.5   216.6 1303.57   226.7 1303.65   236.7 1304.61
   246.7 1306.46   256.7 1308.68   266.7  1311.1   276.8 1313.77   286.8 1316.94
   296.8 1320.66   306.8 1324.89   316.8 1329.56   326.9 1334.71   336.9 1340.21
   346.9 1345.99   356.9 1352.04   366.9 1358.44     377 1365.18     387 1372.13
#Mann= 3 , 0 , 0
       0      .1       0   196.6    .045       0   216.6      .1       0
Bank Sta=196.6,216.6
XS Rating Curve= 0 ,0
Exp/Cntr=0.3,0.1

Type RM Length L Ch R = 1 ,39929.1 ,182.2,186.4,190.7
XS GIS Cut Line= 3
     1705533.133      142431.612     1705554.167      142307.369
     1705661.841      142091.109
#Sta/Elev= 30
     9.7 1358.55    19.4 1354.38    48.5 1341.58    58.2 1337.53    67.9 1334.02
    77.5 1331.05    87.2  1328.3   116.3 1320.79     126 1318.04   146.1 1311.31
   156.2 1308.63   166.3 1306.75   176.3 1305.15   186.5 1303.85   196.5 1303.48
   206.5  1304.7   216.6 1306.43   226.7 1307.88   236.7 1308.91   246.8  1309.6
   256.9 1310.01   287.1 1310.49   297.1 1310.95   307.2 1311.93   317.3 1313.94
   327.3 1316.92   337.4 1320.79   347.5 1325.38   357.5 1330.58   367.6 1336.35
#Mann= 3 , 0 , 0
     9.7      .1       0   186.5    .045       0   206.5      .1       0
Bank Sta=186.5,206.5
XS Rating Curve= 0 ,0
Exp/Cntr=0.3,0.1

Type RM Length L Ch R = 1 ,39742.7 ,255.9,264.7,273.5
XS GIS Cut Line= 4
     1705664.266      142463.279     1705711.477      142382.347
     1705777.234      142299.729     1705902.004      142193.505
#Sta/Elev= 30
     9.4 1319.26    37.5 1313.05    46.8 1311.34    56.2 1310.02      75 1307.87
    84.3 1307.01   103.3 1305.69   112.9 1304.93   131.7 1302.96   141.7 1302.53
   151.7 1302.98   160.9    1304   170.5 1305.33   189.7 1308.19   199.3 1309.78
   218.6  1312.1   228.2 1313.35   247.5 1316.14   257.1 1317.82   266.8 1319.69
   276.4    1322     286 1324.69   295.7  1328.1   305.3 1332.57     315 1340.22
   324.6 1348.98   334.2  1357.9   343.9 1365.78   353.5 1372.74   363.2 1379.61
#Mann= 3 , 0 , 0
       0      .1       0   131.7    .045       0   151.7      .1       0
Bank Sta=131.7,151.7
XS Rating Curve= 0 ,0
Exp/Cntr=0.3,0.1

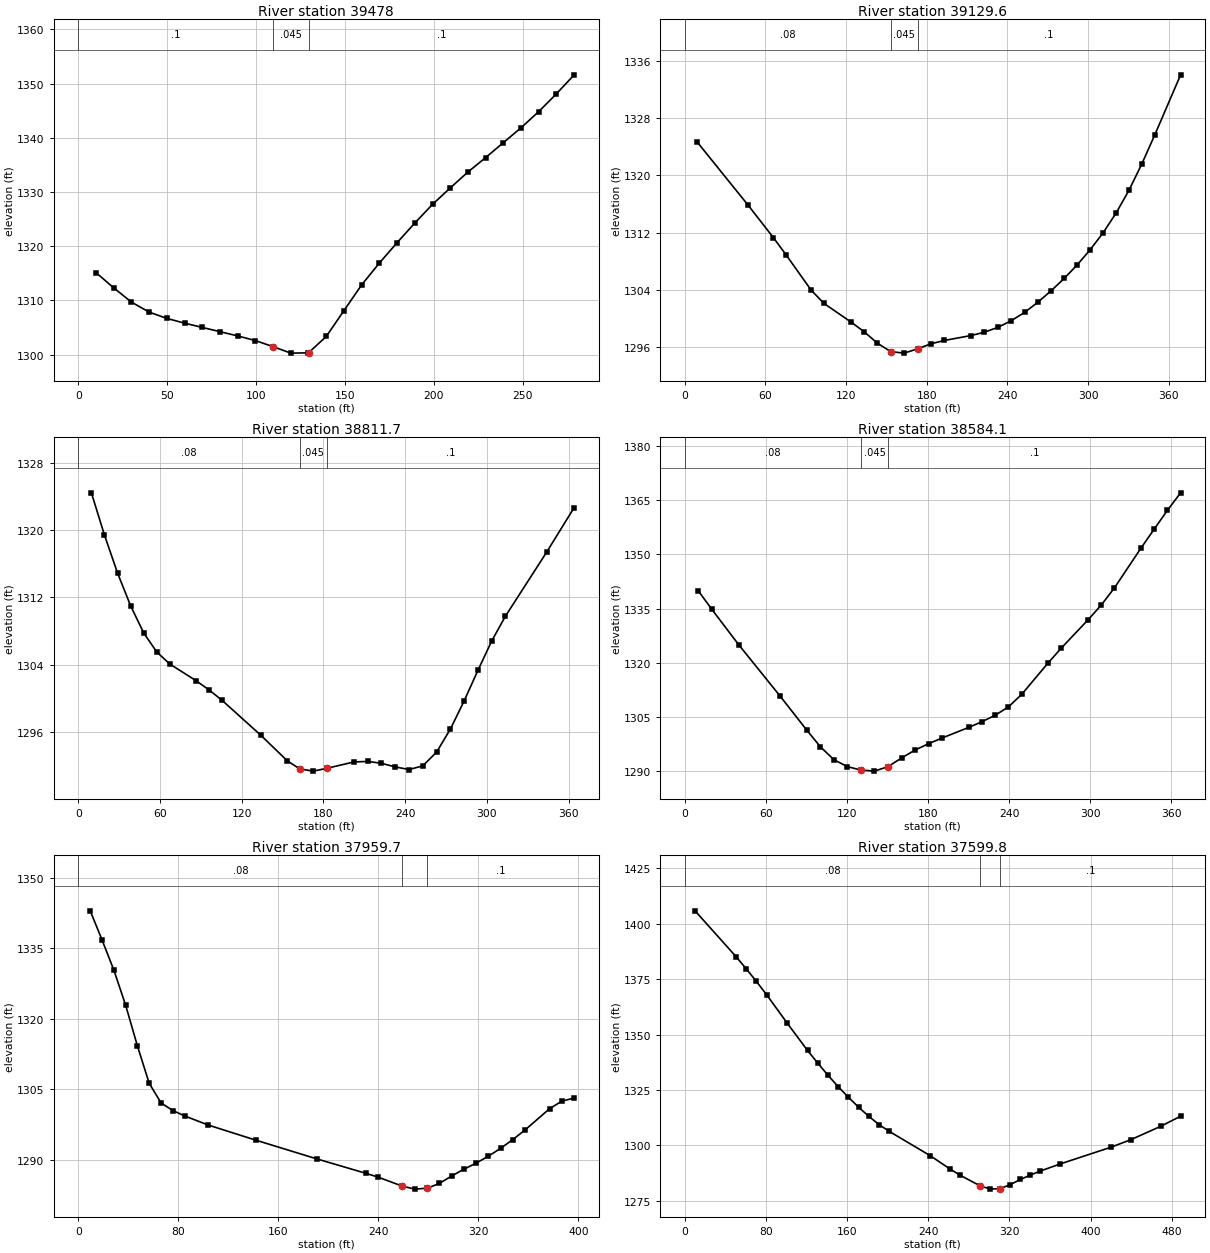
Type RM Length L Ch R = 1 ,39478   ,340.7,348.3,355.9
XS GIS Cut Line= 2
     1705780.606      142598.166     1706030.147      142473.396
#Sta/Elev= 29
      10 1315.13    19.9 1312.33    29.9  1309.7    39.9 1307.85    49.8 1306.69
    59.8 1305.82    69.7 1305.03    79.7 1304.25    89.7 1303.46    99.6 1302.61
   109.6 1301.48   119.6 1300.29   129.5 1300.34   129.6 1300.37   139.5 1303.36
   149.5 1308.15   159.4 1312.87   169.4 1316.91   179.4 1320.68   189.3 1324.28
   199.3 1327.73   209.2 1330.74   219.2 1333.69   229.2 1336.37   239.1  1339.1
   249.1 1341.86   259.1 1344.86     269 1348.12     279 1351.63
#Mann= 3 , 0 , 0
       0      .1       0   109.6    .045       0   129.6      .1       0
Bank Sta=109.6,129.6
XS Rating Curve= 0 ,0
Exp/Cntr=0.3,0.1

Type RM Length L Ch R = 1 ,39129.6 ,323,318,312.6
XS GIS Cut Line= 4
     1705868.283      142872.998     1705969.448      142851.079
     1706138.056       142837.59     1706234.163      142842.648
#Sta/Elev= 30
     9.4 1324.63    47.1 1315.85    65.9 1311.32    75.3 1308.92    94.1 1303.96
   103.5 1302.13   123.4 1299.56   133.4 1298.17   143.3 1296.57   153.2 1295.39
   163.2 1295.18   173.2 1295.78   183.1 1296.48   193.1 1296.95     213 1297.64
   222.9  1298.1   232.9 1298.78   242.8  1299.7   252.8 1300.87   262.7 1302.29
   272.7 1303.92   282.3 1305.62   291.9  1307.5   301.5  1309.6   311.2 1311.98
   320.8 1314.72   330.4 1317.91     340  1321.6   349.7 1325.68   368.9 1334.06
#Mann= 3 , 0 , 0
       0     .08       0   153.2    .045       0   173.2      .1       0
Bank Sta=153.2,173.2
XS Rating Curve= 0 ,0
Exp/Cntr=0.3,0.1

Type RM Length L Ch R = 1 ,38811.7 ,228,227.6,227.5
XS GIS Cut Line= 3
     1705938.131      143212.586     1706110.447      143153.432
     1706281.407      143091.141
#Sta/Elev= 29
     9.6 1324.41    19.2 1319.39    28.8 1314.89    38.4    1311    47.9 1307.81
    57.5 1305.54    67.1  1304.1    86.3 1302.13    95.9 1301.03   105.5 1299.79
   134.2 1295.61   153.4 1292.61   162.6 1291.64   172.6 1291.38   182.6 1291.72
   202.4 1292.47   212.5 1292.53   222.6 1292.31   232.7 1291.88   242.8 1291.57
   252.9    1292   263.1 1293.64   273.2 1296.37   283.3 1299.71   293.4 1303.33
   303.5 1306.81   313.6 1309.76   343.9 1317.37   364.1 1322.66
#Mann= 3 , 0 , 0
       0     .08       0   162.6    .045       0   182.6      .1       0
Bank Sta=162.6,182.6
XS Rating Curve= 0 ,0
Exp/Cntr=0.3,0.1

Type RM Length L Ch R = 1 ,38584.1 ,623.6,624.4,625.2
XS GIS Cut Line= 3
     1706028.461      143424.348     1706207.186      143358.591
      1706370.65      143292.397
#Sta/Elev= 29
      10 1339.91      20 1334.78    40.1 1324.86    70.2 1310.85    90.2 1301.29
   100.2 1296.69   110.3 1293.06   120.3 1291.13   130.3 1290.19   140.3 1289.89
   150.3 1291.13   160.4 1293.55   170.4 1295.75   180.4 1297.51   190.4 1299.09
     210 1302.01   219.8  1303.6   229.6 1305.38   239.4 1307.71   249.2 1311.17
   268.8 1319.92   278.6 1324.06   298.2 1331.83     308 1335.93   317.8 1340.72
   337.4 1351.73   347.2 1357.01     357 1362.24   366.8 1367.11
#Mann= 3 , 0 , 0
       0     .08       0   130.3    .045       0   150.3      .1       0
Bank Sta=130.3,150.3
XS Rating Curve= 0 ,0
Exp/Cntr=0.3,0.1

Type RM Length L Ch R = 1 ,37959.7 ,380.5,359.9,339.3
XS GIS Cut Line= 3
     1706074.285      143987.401     1706215.616      143999.304
     1706458.413      143921.744
#Sta/Elev= 28
     9.5 1342.93    18.9 1336.79    28.4 1330.34    37.8 1322.91    47.3 1314.17
    56.7 1306.26    66.2 1302.08    75.6 1300.46    85.1 1299.31     104 1297.37
   141.8 1294.18   190.8 1290.18   230.1 1287.11   239.9 1286.29   259.3 1284.38
   269.3 1283.75   279.3 1283.95   288.9 1284.97   298.7 1286.54   308.5 1287.99
   318.3 1289.28   328.1 1290.76   337.9 1292.43   347.7  1294.3   357.5 1296.35
   377.1 1300.87   386.9 1302.46   396.7 1303.12
#Mann= 3 , 0 , 0
       0     .08       0   259.3    .045       0   279.3      .1       0
Bank Sta=259.3,279.3
XS Rating Curve= 0 ,0
Exp/Cntr=0.3,0.1

Type RM Length L Ch R = 1 ,37599.8 ,387.9,392.4,397.9
XS GIS Cut Line= 3
     1706443.234      144494.055     1706547.775      144275.822
     1706610.637      144037.097
#Sta/Elev= 30
    10.1 1405.79    50.4 1385.18    60.5 1379.67    70.6 1373.95    80.7 1367.93
   100.8 1355.23     121  1342.8   131.1 1337.09   141.2 1331.58   151.2 1326.48
   161.3 1321.69   171.4 1317.19   181.5 1313.06   191.6 1309.34   201.7 1306.27
     242 1295.33   261.7 1289.26   271.6 1286.49   291.2 1281.72   301.2 1280.26
   311.2 1280.54     321 1282.34   330.9 1284.61   340.7 1286.62   350.6 1288.44
   370.3 1291.65   419.7  1299.1   439.5 1302.52   469.1 1308.58   488.8 1313.15
#Mann= 3 , 0 , 0
       0     .08       0   291.2    .045       0   311.2      .1       0
Bank Sta=291.2,311.2
XS Rating Curve= 0 ,0
Exp/Cntr=0.3,0.1

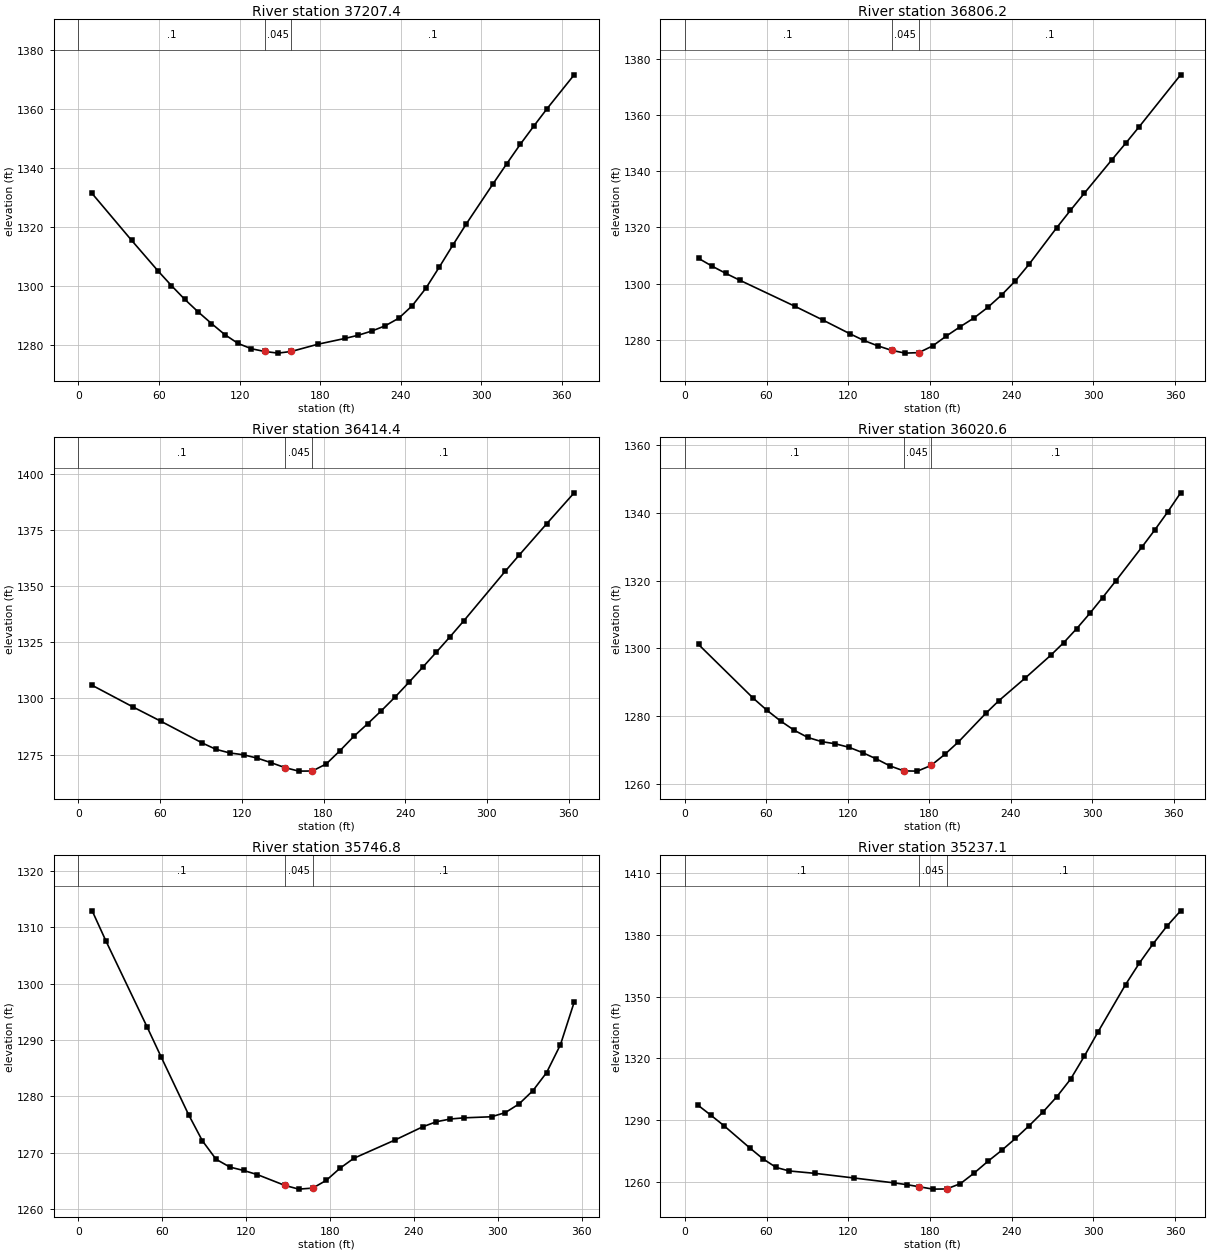
Type RM Length L Ch R = 1 ,37207.4 ,401.4,401.2,400
XS GIS Cut Line= 3
     1706858.692      144391.052      1706945.71      144224.166
     1707037.432      144068.239
#Sta/Elev= 30
     9.9 1331.56    39.6  1315.5    59.4 1305.04    69.3  1300.1    79.2 1295.44
    89.2 1291.17    99.1 1287.23     109 1283.47   118.9 1280.46   128.8 1278.66
   138.6 1277.74   148.6 1277.17   158.6 1277.74   178.3 1280.19   198.3 1282.14
   208.3 1283.24   218.4 1284.66   228.4 1286.44   238.5 1289.01   248.5 1293.24
   258.6 1299.13   268.6 1306.31   278.7 1313.78   288.7 1320.98   308.8 1334.71
   318.9 1341.47   328.9 1348.02     339 1354.23     349 1360.22   369.1 1371.67
#Mann= 3 , 0 , 0
       0      .1       0   138.6    .045       0   158.6      .1       0
Bank Sta=138.6,158.6
XS Rating Curve= 0 ,0
Exp/Cntr=0.3,0.1

Type RM Length L Ch R = 1 ,36806.2 ,384.5,391.8,399.2
XS GIS Cut Line= 3
      1707195.17      144606.966     1707277.912      144444.862
     1707360.653      144282.757
#Sta/Elev= 27
    10.1 1308.98    20.2 1306.15    30.3 1303.58    40.4 1301.17    80.9 1291.87
   101.1 1287.04   121.3 1282.06   131.4  1279.7   141.6 1277.78   151.8 1276.17
   161.8 1275.17   171.8 1275.35     182 1277.76   192.1  1281.3   202.2  1284.6
   212.3 1287.71   222.4 1291.48   232.6 1295.93   242.7 1300.96   252.8 1306.91
     273  1319.9   283.1  1326.1   293.2 1332.16   313.4 1344.08   323.6 1350.01
   333.7 1356.01     364 1374.46
#Mann= 3 , 0 , 0
       0      .1       0   151.8    .045       0   171.8      .1       0
Bank Sta=151.8,171.8
XS Rating Curve= 0 ,0
Exp/Cntr=0.3,0.1

Type RM Length L Ch R = 1 ,36414.4 ,402.5,393.8,385.2
XS GIS Cut Line= 3
     1707459.188      144806.994     1707594.592      144685.381
     1707729.996      144563.768
#Sta/Elev= 27
    10.1 1305.89    40.4 1296.14    60.7 1289.83      91 1280.16   101.1 1277.33
   111.2 1275.73   121.3 1274.91   131.4 1273.41   141.6 1271.37   151.8 1269.18
   161.8 1267.63   171.8 1267.69     182 1270.83   192.1 1276.75   202.2  1283.1
   212.3 1288.69   222.4 1294.52   232.6 1300.69   242.7 1307.21   252.8 1313.91
   262.9 1320.69     273  1327.6   283.1  1334.7   313.4 1356.71   323.6 1363.88
   343.8 1377.86     364 1391.66
#Mann= 3 , 0 , 0
       0      .1       0   151.8    .045       0   171.8      .1       0
Bank Sta=151.8,171.8
XS Rating Curve= 0 ,0
Exp/Cntr=0.3,0.1

Type RM Length L Ch R = 1 ,36020.6 ,276.6,273.8,270.9
XS GIS Cut Line= 3
     1707815.648      145098.029     1707903.389      144894.615
     1707977.134      144771.721
#Sta/Elev= 30
    10.1 1301.16    50.3 1285.31    60.4 1281.74    70.5 1278.55    80.6  1275.8
    90.6 1273.68   100.7 1272.46   110.8 1271.81   120.8 1270.79   130.9  1269.2
     141 1267.34     151 1265.28   161.2 1263.81   171.2 1263.74   181.2 1265.41
   191.3 1268.67   201.4 1272.38   221.5 1280.81   231.1 1284.54   250.2 1291.13
   269.3 1297.97   278.9 1301.72   288.4 1305.84     298 1310.32   307.5 1315.04
   317.1  1319.9   336.2 1329.84   345.7  1334.9   355.3 1340.27   364.9 1345.97
#Mann= 3 , 0 , 0
       0      .1       0   161.2    .045       0   181.2      .1       0
Bank Sta=161.2,181.2
XS Rating Curve= 0 ,0
Exp/Cntr=0.3,0.1

Type RM Length L Ch R = 1 ,35746.8 ,499.1,509.7,521
XS GIS Cut Line= 2
     1708088.858      145208.227     1708181.593      144865.952
#Sta/Elev= 28
     9.9  1312.9    19.7 1307.57    49.3 1292.23    59.1 1287.04    78.8 1276.76
    88.7  1272.1    98.5 1268.82   108.4 1267.43   118.2 1266.83   128.1 1266.09
   147.6 1264.19   157.6 1263.52   167.6  1263.7   177.3 1265.07   187.2 1267.24
     197 1268.99   226.6 1272.25   246.3 1274.58   256.1 1275.48     266 1275.96
   275.8 1276.17   295.5 1276.36   305.4  1277.1   315.2 1278.64   325.1 1280.99
   334.9  1284.2   344.8 1289.15   354.6 1296.69
#Mann= 3 , 0 , 0
       0      .1       0   147.6    .045       0   167.6      .1       0
Bank Sta=147.6,167.6
XS Rating Curve= 0 ,0
Exp/Cntr=0.3,0.1

Type RM Length L Ch R = 1 ,35237.1 ,416,422.7,428.7
XS GIS Cut Line= 3
     1708472.664       145301.29     1708598.591      145169.673
     1708729.229      145042.994
#Sta/Elev= 30
     9.6 1297.34    19.2 1292.42    28.8 1287.34    47.9 1276.47    57.5 1271.25
    67.1  1267.1    76.7 1265.41    95.9 1264.23   124.6 1261.97   153.4 1259.65
     163 1258.77   172.2 1257.75   182.2  1256.6   192.2 1256.68   202.4 1259.26
   212.5 1264.41   222.6  1270.1   232.7  1275.4   242.8 1281.16   252.9 1287.39
     263 1293.98   273.1 1301.34   283.3 1309.93   293.4 1321.09   303.5 1332.89
   323.7 1355.82   333.8  1366.2   343.9 1375.57     354 1384.09   364.1 1391.55
#Mann= 3 , 0 , 0
       0      .1       0   172.2    .045       0   192.2      .1       0
Bank Sta=172.2,192.2
XS Rating Curve= 0 ,0
Exp/Cntr=0.3,0.1

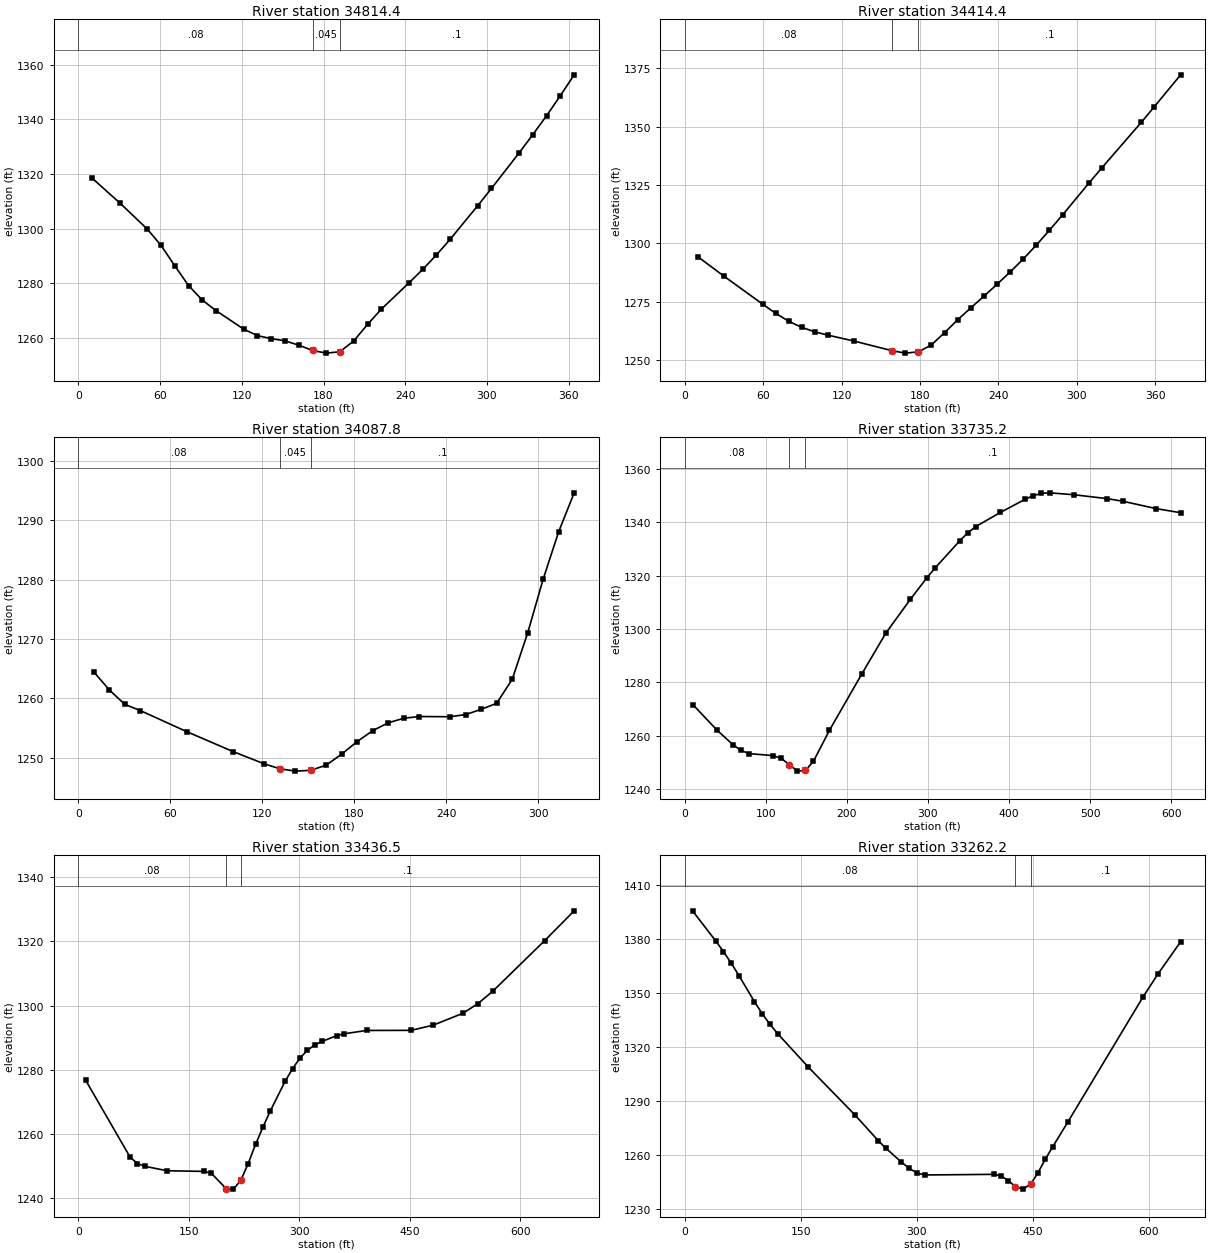
Type RM Length L Ch R = 1 ,34814.4 ,427.9,400,374.1
XS GIS Cut Line= 3
     1708627.078      145619.214     1708789.639      145537.374
     1708951.757      145454.651
#Sta/Elev= 30
    10.1 1318.52    30.3  1309.5    50.6 1299.88    60.7 1293.88    70.8 1286.42
    80.9 1279.18      91 1273.87   101.1 1269.99   121.3 1263.25   131.4 1260.85
   141.6 1259.74   151.7 1258.93   161.8 1257.35     172  1255.4     182 1254.43
     192 1254.93   202.2  1258.9   212.3 1264.94   222.4 1270.52   242.7 1280.14
   252.8 1285.09   262.9 1290.39     273 1296.14   293.2 1308.43   303.3 1314.76
   323.6 1327.77   333.7  1334.5   343.8 1341.42   353.9 1348.75     364 1356.36
#Mann= 3 , 0 , 0
       0     .08       0     172    .045       0     192      .1       0
Bank Sta=172,192
XS Rating Curve= 0 ,0
Exp/Cntr=0.3,0.1

Type RM Length L Ch R = 1 ,34414.4 ,330.2,326.6,321.1
XS GIS Cut Line= 3
     1709140.955      145897.818     1709092.044      145725.931
     1709055.069      145528.724
#Sta/Elev= 28
     9.9 1294.35    29.8 1286.07    59.6 1274.02    69.5 1270.12    79.4 1266.76
    89.4 1264.12    99.3 1262.24   109.2 1260.82   129.1  1258.3   158.8  1254.1
   168.8 1253.09   178.8 1253.63   188.7  1256.6   198.8 1261.87   208.8 1267.34
   218.8 1272.43   228.9 1277.43   238.9  1282.5   248.9 1287.77     259 1293.34
     269  1299.3     279 1305.63   289.1 1312.21   309.1 1325.72   319.2 1332.37
   349.3 1351.78   359.3 1358.48   379.4  1372.1
#Mann= 3 , 0 , 0
       0     .08       0   158.8    .045       0   178.8      .1       0
Bank Sta=158.8,178.8
XS Rating Curve= 0 ,0
Exp/Cntr=0.3,0.1

Type RM Length L Ch R = 1 ,34087.8 ,359.3,352.6,345.9
XS GIS Cut Line= 2
     1709441.099      145730.914     1709304.526      145437.535
#Sta/Elev= 26
    10.1 1264.45    20.2 1261.43    30.3 1258.99    40.5 1257.94    70.8 1254.39
   101.1 1251.03   121.4 1248.97   131.6 1248.14   141.6 1247.75   151.6 1247.88
   161.8 1248.76   171.9 1250.62     182 1252.73   192.1 1254.56   202.3 1255.89
   212.4 1256.65   222.5 1256.94   242.7 1256.91   252.8 1257.27   262.9 1258.15
     273 1259.16   283.2 1263.22   293.3 1271.05   303.4 1280.09   313.5 1288.06
   323.6  1294.6
#Mann= 3 , 0 , 0
       0     .08       0   131.6    .045       0   151.6      .1       0
Bank Sta=131.6,151.6
XS Rating Curve= 0 ,0
Exp/Cntr=0.3,0.1

Type RM Length L Ch R = 1 ,33735.2 ,287.9,298.7,309.5
XS GIS Cut Line= 3
     1709759.769      145510.037     1709583.721      145335.385
     1709489.996      144983.978
#Sta/Elev= 30
     9.9 1271.73    39.7 1262.15    59.5 1256.67    69.4 1254.54    79.4 1253.35
   109.1 1252.61     119 1251.56   128.9 1249.26   138.9 1246.79   148.9 1247.07
   158.7 1250.47   178.5 1262.11   218.2 1283.11     248 1298.48   278.3 1311.17
   298.5 1319.15   308.6 1322.84   338.9 1332.98     349 1336.03   359.1 1338.44
   389.4 1343.72   419.7 1348.61   429.8 1350.01   439.9 1350.85     450 1351.06
   480.3 1350.34   520.8 1348.89     541 1347.87   581.4 1345.15   611.7 1343.61
#Mann= 3 , 0 , 0
       0     .08       0   128.9    .045       0   148.9      .1       0
Bank Sta=128.9,148.9
XS Rating Curve= 0 ,0
Exp/Cntr=0.3,0.1

Type RM Length L Ch R = 1 ,33436.5 ,170.1,174.2,178.4
XS GIS Cut Line= 3
     1709933.436       145422.36     1709860.935      145140.784
       1709768.2      144769.845
#Sta/Elev= 30
      10 1276.75    70.2 1252.85    80.2 1250.82    90.2 1249.97   120.3 1248.59
   170.4 1248.38   180.5 1247.81   200.6 1243.04   210.6 1242.86   220.6 1245.62
   230.6 1250.84   240.6 1256.79   250.7 1262.22   260.7 1267.25   280.7 1276.43
   290.8 1280.35   300.8 1283.65   310.9 1286.08   320.9 1287.76     331 1288.87
   351.1 1290.68   361.2 1291.25   391.4 1292.27   451.8  1292.3   481.9 1293.93
   522.2 1297.63   542.3  1300.6   562.4 1304.44   632.9  1320.2   673.1 1329.52
#Mann= 3 , 0 , 0
       0     .08       0   200.6    .045       0   220.6      .1       0
Bank Sta=200.6,220.6
XS Rating Curve= 0 ,0
Exp/Cntr=0.3,0.1

Type RM Length L Ch R = 1 ,33262.2 ,492.7,507,521.4
XS GIS Cut Line= 4
     1710072.639      145619.852     1710051.231      145230.615
     1710047.339      145144.983     1710043.446      144979.557
#Sta/Elev= 30
      10 1395.86      40  1379.1      50 1373.18      60 1366.76      70 1359.86
      90 1345.37     100 1338.66     110 1332.81   119.9 1327.63   159.9 1308.85
   219.9 1282.38   249.9 1268.13   259.9 1263.84   279.9 1256.18   289.9 1252.68
   299.9 1250.11   309.9 1248.96   399.3 1249.31   408.9 1248.47   418.4 1245.77
   427.4  1242.5   437.4 1241.09   447.4 1243.97   456.5 1250.15     466 1257.66
   475.5 1264.57     495 1278.26   592.3  1347.9   611.8 1360.82     641 1378.64
#Mann= 3 , 0 , 0
       0     .08       0   427.4    .045       0   447.4      .1       0
Bank Sta=427.4,447.4
XS Rating Curve= 0 ,0
Exp/Cntr=0.3,0.1

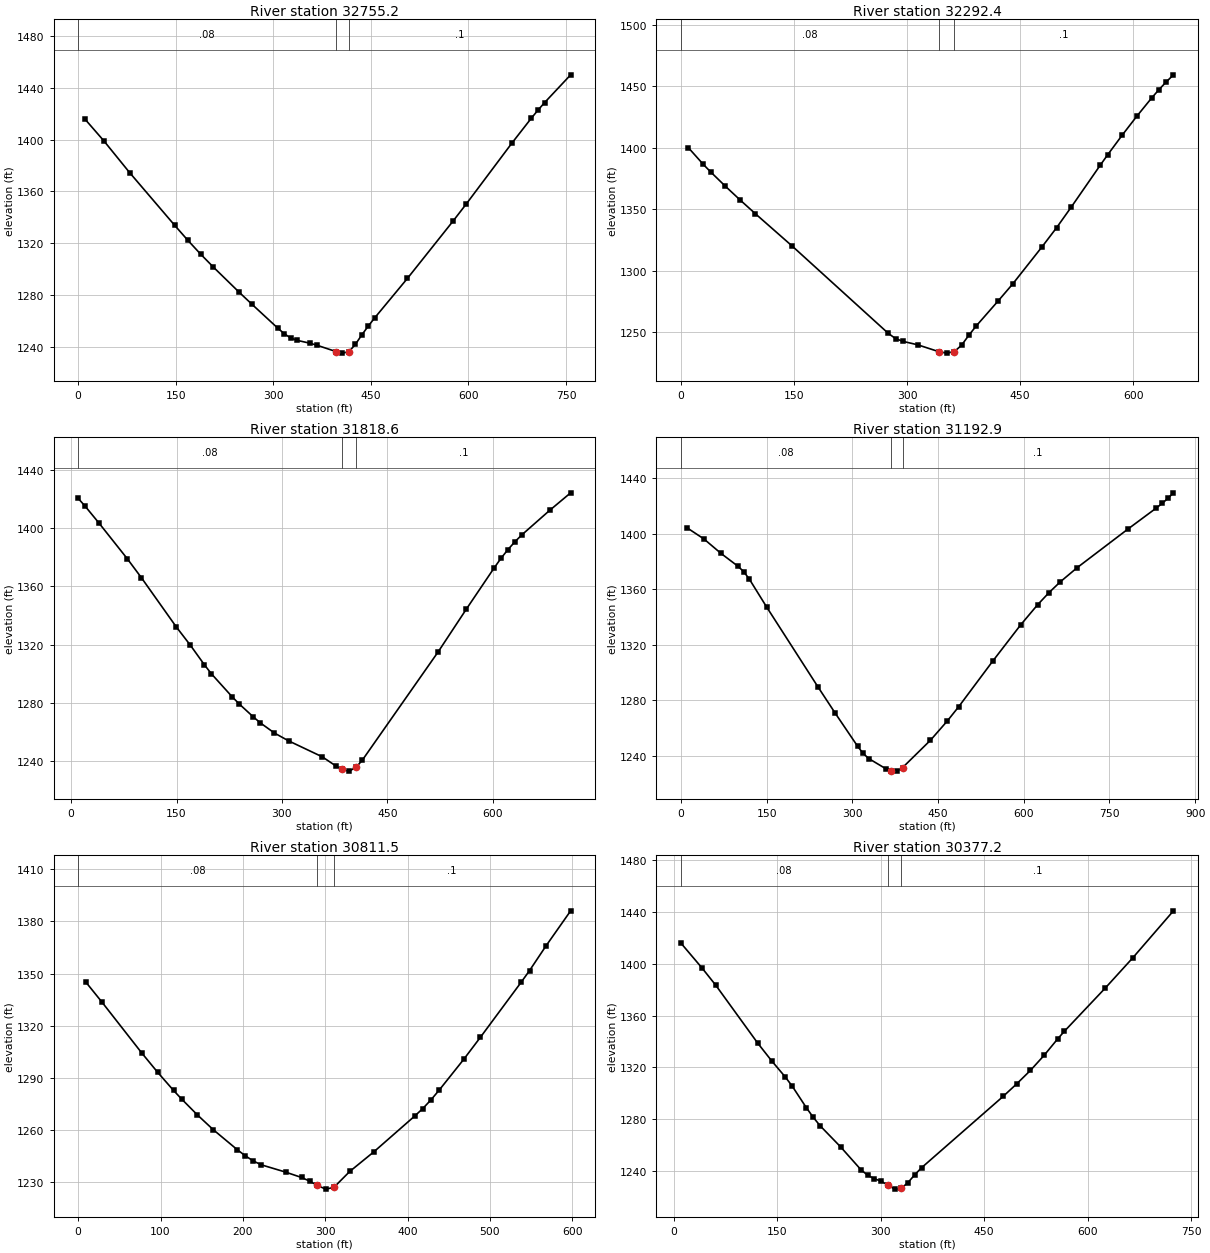
Type RM Length L Ch R = 1 ,32755.2 ,460.6,462.8,464.9
XS GIS Cut Line= 4
     1710232.226      145736.623     1710395.706      145512.812
     1710506.638      145372.686     1710635.087       145100.22
#Sta/Elev= 30
     9.9  1416.1    39.6 1398.95    79.2 1374.43   148.5 1333.71   168.3 1322.38
   188.1 1311.61   207.9  1301.5   247.5 1282.11   267.3 1272.75   306.9 1254.38
   316.9 1250.03   326.8 1246.74   336.7 1244.95   356.6  1242.7   366.5 1241.28
   396.2 1236.33   406.2 1235.09   416.2 1236.18   426.1 1241.81     436 1249.13
     446    1256   455.9 1262.34   506.1 1292.76   576.4 1337.11   596.5 1350.18
   666.7 1397.22   696.9 1416.68   706.9 1422.75   716.9 1428.48   757.1    1450
#Mann= 3 , 0 , 0
       0     .08       0   396.2    .045       0   416.2      .1       0
Bank Sta=396.2,416.2
XS Rating Curve= 0 ,0
Exp/Cntr=0.3,0.1

Type RM Length L Ch R = 1 ,32292.4 ,476.6,473.8,471
XS GIS Cut Line= 4
     1710557.239      146011.035      1710714.88      145822.255
     1710851.113      145684.076     1711028.216      145565.359
#Sta/Elev= 30
     9.8 1400.08    29.5 1386.58    39.4 1380.37      59  1368.7    78.7 1357.45
    98.4 1346.58   147.6  1320.1   275.1 1249.16   284.8 1244.91   294.5 1242.71
   313.9 1239.95   342.7 1234.22   352.7 1233.17   362.7 1234.48   372.1 1239.54
   381.8 1247.67   391.5 1255.17   420.6  1275.5     440 1289.36   478.8 1319.46
   498.1 1334.98   517.5 1351.69   556.3 1386.01     566 1394.36   585.4  1410.4
   604.7  1425.7   624.1 1440.31   633.8 1447.13   643.5 1453.43   653.2 1459.26
#Mann= 3 , 0 , 0
       0     .08       0   342.7    .045       0   362.7      .1       0
Bank Sta=342.7,362.7
XS Rating Curve= 0 ,0
Exp/Cntr=0.3,0.1

Type RM Length L Ch R = 1 ,31818.6 ,617.7,625.8,633.8
XS GIS Cut Line= 4
      1710812.19      146388.595     1711043.786      146168.676
     1711117.741      146069.421      1711322.09       145896.21
#Sta/Elev= 30
      10 1420.32      20  1414.9    39.9 1403.21    79.8 1378.96    99.8 1366.01
   149.7 1332.08   169.7 1319.55   189.6 1306.18   199.6 1299.96   229.6 1283.95
   239.5 1279.12   259.5 1270.28   269.5 1266.19   289.4 1259.28   309.4 1253.95
   357.5 1242.96   376.5 1236.79   385.5 1234.35   395.5 1233.15   405.5  1235.7
   414.6 1240.78   522.5 1315.07   562.2 1344.09   601.9 1372.45   611.8 1379.17
   621.7 1385.16   631.7 1390.57   641.6 1395.31   681.3 1412.16     711 1424.12
#Mann= 3 , 0 , 0
      10     .08       0   385.5    .045       0   405.5      .1       0
Bank Sta=385.5,405.5
XS Rating Curve= 0 ,0
Exp/Cntr=0.3,0.1

Type RM Length L Ch R = 1 ,31192.9 ,372,381.3,390.6
XS GIS Cut Line= 4
     1711162.503      146744.747     1711401.884      146620.192
     1711571.202      146520.936     1711886.484      146281.555
#Sta/Elev= 30
      10 1404.52      40 1396.36      70 1385.91    99.9 1376.58   109.9  1372.7
   119.9  1367.2   149.9 1347.27   239.9 1289.56   269.8 1270.81   309.1 1246.89
   318.9 1241.65   328.7 1237.97   358.2 1230.72   367.8 1229.09   377.8 1228.91
   387.8 1231.42   436.7 1251.19   466.1 1265.03   485.9 1275.24   545.3 1308.01
   594.8 1334.48   624.5 1348.99   644.3 1357.66     664 1365.41   693.7 1375.68
   782.8 1403.58   832.3  1418.7   842.2 1421.92   852.1 1425.52     862 1429.56
#Mann= 3 , 0 , 0
       0     .08       0   367.8    .045       0   387.8      .1       0
Bank Sta=367.8,387.8
XS Rating Curve= 0 ,0
Exp/Cntr=0.3,0.1

Type RM Length L Ch R = 1 ,30811.5 ,438.5,434.3,430.1
XS GIS Cut Line= 4
     1711366.853       146937.42     1711540.063      146923.797
     1711744.413      146910.173     1711956.547      146853.734
#Sta/Elev= 30
     9.7 1344.87      29 1333.53    77.2 1304.37    96.5 1293.26   115.8 1282.84
   125.5 1277.95   144.8 1268.74   164.1 1260.24   193.3 1248.73     203 1245.25
   212.8 1242.23   222.5 1240.05   251.8 1235.89   271.3 1232.78     281 1230.72
   290.5 1228.24   300.5 1226.09   310.5 1227.07   329.8 1236.24     359 1247.49
   408.5 1268.01   418.5 1272.39   428.4 1277.37   438.4 1282.98   468.3 1300.73
   488.3 1313.25   538.2 1345.15   548.2 1351.74   568.1 1365.86   598.1 1386.06
#Mann= 3 , 0 , 0
       0     .08       0   290.5    .045       0   310.5      .1       0
Bank Sta=290.5,310.5
XS Rating Curve= 0 ,0
Exp/Cntr=0.3,0.1

Type RM Length L Ch R = 1 ,30377.2 ,340.2,335.2,330.1
XS GIS Cut Line= 4
     1711349.337      147408.397     1711559.525      147379.204
     1711738.574      147328.603     1712046.072      147219.617
#Sta/Elev= 30
    10.1 1415.94    40.4 1396.93    60.6 1383.45   121.3 1338.86   141.5  1325.2
   161.7 1312.46   171.8 1305.31     192 1288.92   202.1 1281.41   212.2 1274.85
   241.6 1258.73     271 1241.16   280.8 1236.81   290.5 1234.18   300.3 1232.17
   309.9 1229.42   319.9 1226.07   329.9 1226.77   339.5 1231.18   349.3 1237.21
   359.1 1242.58   477.4 1297.63   497.1 1307.31   516.9 1317.64   536.7 1329.22
   556.4 1341.94   566.3 1347.93   625.6 1381.27   665.2 1404.43   724.5 1440.89
#Mann= 3 , 0 , 0
    10.1     .08       0   309.9    .045       0   329.9      .1       0
Bank Sta=309.9,329.9
XS Rating Curve= 0 ,0
Exp/Cntr=0.3,0.1

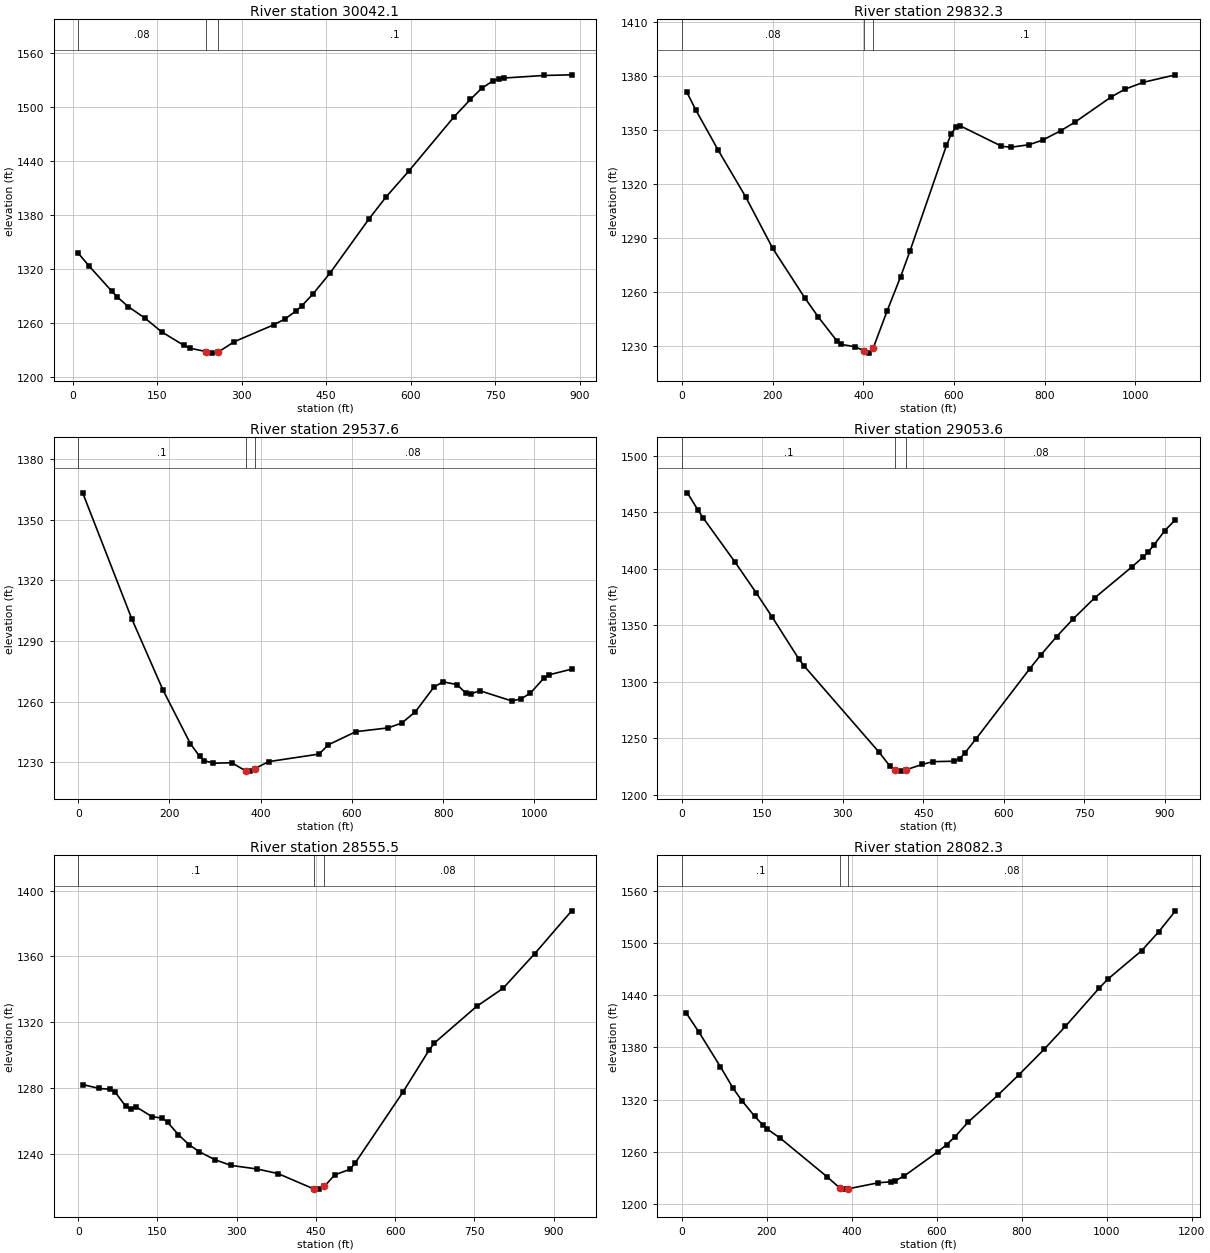
Type RM Length L Ch R = 1 ,30042.1 ,207.7,209.8,211.8
XS GIS Cut Line= 4
     1711628.216      147737.198     1711693.812      147715.894
     1711907.892      147591.338     1712382.762      147278.002
#Sta/Elev= 30
     9.9 1337.25    29.6 1322.74      69  1295.3    78.9 1288.77    98.7 1277.75
   128.4    1265   158.1 1249.67   197.8 1234.55   207.7 1231.56   237.3 1227.75
   247.3 1226.05   257.3 1226.79   286.9 1238.77   356.6 1257.49   376.5 1263.97
   396.5 1272.93   406.5  1278.6   426.4 1291.77   456.4 1314.81   526.3 1375.75
   556.2 1399.84   596.1 1428.35     676  1488.4   705.9 1508.44   725.9 1520.78
   745.8 1529.04   755.8 1531.19   765.8 1532.25   835.7 1535.08   885.6 1535.81
#Mann= 3 , 0 , 0
     9.9     .08       0   237.3    .045       0   257.3      .1       0
Bank Sta=237.3,257.3
XS Rating Curve= 0 ,0
Exp/Cntr=0.3,0.1

Type RM Length L Ch R = 1 ,29832.3 ,283.3,294.7,306.1
XS GIS Cut Line= 4
     1711602.021      147849.995     1711832.073       147853.59
     1712033.369      147760.131     1712570.475      147418.686
#Sta/Elev= 30
      10 1371.32      30 1361.32      80 1338.66     140 1312.97   200.1  1284.1
   270.4 1256.75   300.7 1245.92     341 1232.85   351.1 1230.72   381.4 1229.44
   401.7 1227.11   411.7 1225.87   421.7 1228.66     452 1249.11   482.3 1268.48
   502.5 1282.48   583.3 1341.44   593.4 1347.51   603.5 1351.43   613.7 1352.32
   704.6 1341.01   724.8 1340.41   765.2 1341.81   795.5 1344.39   835.9 1349.69
   866.2 1354.29     947 1368.46   977.3 1372.75  1017.7 1376.56  1088.5 1380.71
#Mann= 3 , 0 , 0
       0     .08       0   401.7    .045       0   421.7      .1       0
Bank Sta=401.7,421.7
XS Rating Curve= 0 ,0
Exp/Cntr=0.3,0.1

Type RM Length L Ch R = 1 ,29537.6 ,482.2,484,485.9
XS GIS Cut Line= 4
     1711738.955      147987.288     1711933.978      148004.065
     1712282.084      148058.587     1712766.325      147834.675
#Sta/Elev= 30
     9.8 1363.34   117.4 1300.96     186 1265.64   246.1 1239.06   266.2 1232.85
   276.3 1230.78   296.4 1229.47   336.7 1229.72     367 1225.66     377 1225.56
     387 1226.78   417.2 1230.25     528 1234.01   548.1 1238.57   608.5 1245.09
     679 1246.96   709.2 1249.35   739.3    1255   779.6 1267.14   799.7 1269.79
   829.9  1268.4   850.1 1264.17   860.1 1263.76   880.3 1265.36   950.7 1260.29
   970.9 1261.35     991 1264.15  1021.2 1271.71  1031.3  1273.2  1081.6 1276.05
#Mann= 3 , 0 , 0
       0      .1       0     367    .045       0     387     .08       0
Bank Sta=367,387
XS Rating Curve= 0 ,0
Exp/Cntr=0.3,0.1

Type RM Length L Ch R = 1 ,29053.6 ,496,498.1,500.1
XS GIS Cut Line= 4
     1711565.338      148356.561     1711831.336      148435.642
     1712115.307       148496.75     1712467.574      148500.344
#Sta/Elev= 30
     9.9 1467.04    29.7 1451.82    39.6 1444.72    99.1 1405.64   138.8 1378.33
   168.5 1357.01     218  1320.1   227.9 1313.94   367.7 1237.73   387.7 1225.58
   397.7 1221.71   407.7 1221.15   417.7 1222.31   447.8 1227.06   467.8 1229.52
   507.9  1229.9   517.9 1232.25   527.9 1237.42   547.9 1249.43   648.5 1311.64
   668.6 1323.53   698.8 1340.08     729 1355.43   769.3  1374.1   839.7 1401.86
   859.9  1410.3   869.9 1415.09     880 1420.86   900.1 1433.48   920.3 1443.45
#Mann= 3 , 0 , 0
       0      .1       0   397.7    .045       0   417.7     .08       0
Bank Sta=397.7,417.7
XS Rating Curve= 0 ,0
Exp/Cntr=0.3,0.1

Type RM Length L Ch R = 1 ,28555.5 ,479.7,473.2,466.7
XS GIS Cut Line= 4
     1711435.934      148759.153     1711748.661      148913.719
     1711924.795      148971.232     1712323.792      148996.394
#Sta/Elev= 30
      10 1282.03    39.9 1279.77    59.8 1279.31    69.8 1277.63    89.7 1269.02
    99.7 1267.32   109.6 1268.58   139.5 1262.69   159.5 1261.67   169.4 1259.15
   189.4 1251.78   209.3 1245.71   229.2 1241.32   259.1 1236.43     289 1233.03
   338.9 1230.82   378.1 1228.05   446.1 1218.68   456.1  1218.6   466.1 1220.34
   485.4 1227.24   514.6 1230.68   524.4 1234.61   614.1 1277.33   664.1  1303.1
   674.1 1307.41     754 1329.65     804 1340.62     864  1361.7   933.9 1387.74
#Mann= 3 , 0 , 0
       0      .1       0   446.1    .045       0   466.1     .08       0
Bank Sta=446.1,466.1
XS Rating Curve= 0 ,0
Exp/Cntr=0.3,0.1

Type RM Length L Ch R = 1 ,28082.3 ,666.2,664.3,662.3
XS GIS Cut Line= 4
     1711292.151      149384.607     1711583.311      149384.607
     1711885.255      149384.607     1712453.196      149413.364
#Sta/Elev= 30
      10 1419.57    40.2 1397.36    90.4 1357.73   120.5 1332.81   140.6 1318.94
   170.7 1300.97   190.8 1290.35   200.8 1285.92   230.9 1275.69   341.5 1231.08
   371.7 1218.05   381.7 1216.87   391.7 1217.32   462.3 1224.21   492.5 1225.36
   502.5 1226.71   522.6 1231.86   603.1 1260.18     623 1268.12     643 1277.34
   672.9 1293.78   742.8 1324.71   792.6 1348.29   852.5  1377.9   902.4 1404.22
   982.2 1448.42  1002.1 1458.55    1082 1491.47  1121.9 1513.05  1161.8  1537.4
#Mann= 3 , 0 , 0
       0      .1       0   371.7    .045       0   391.7     .08       0
Bank Sta=371.7,391.7
XS Rating Curve= 0 ,0
Exp/Cntr=0.3,0.1