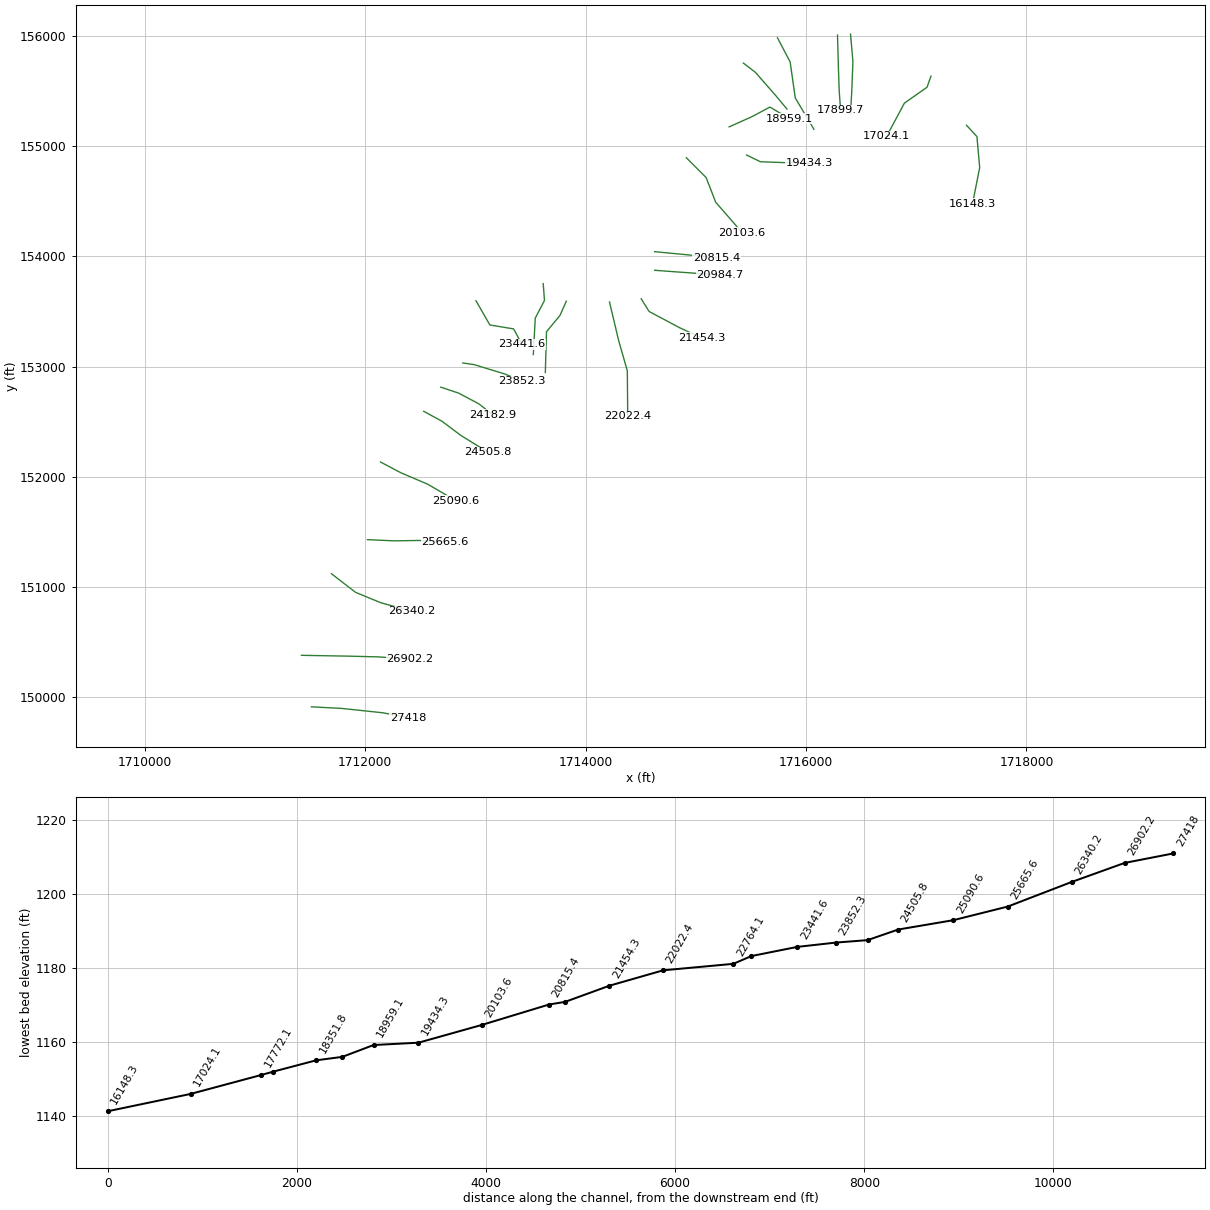
HEC-RAS study Panther Creek.prj: Panther Creek

--- Panther Creek.g01 (geometry) --- (continued)

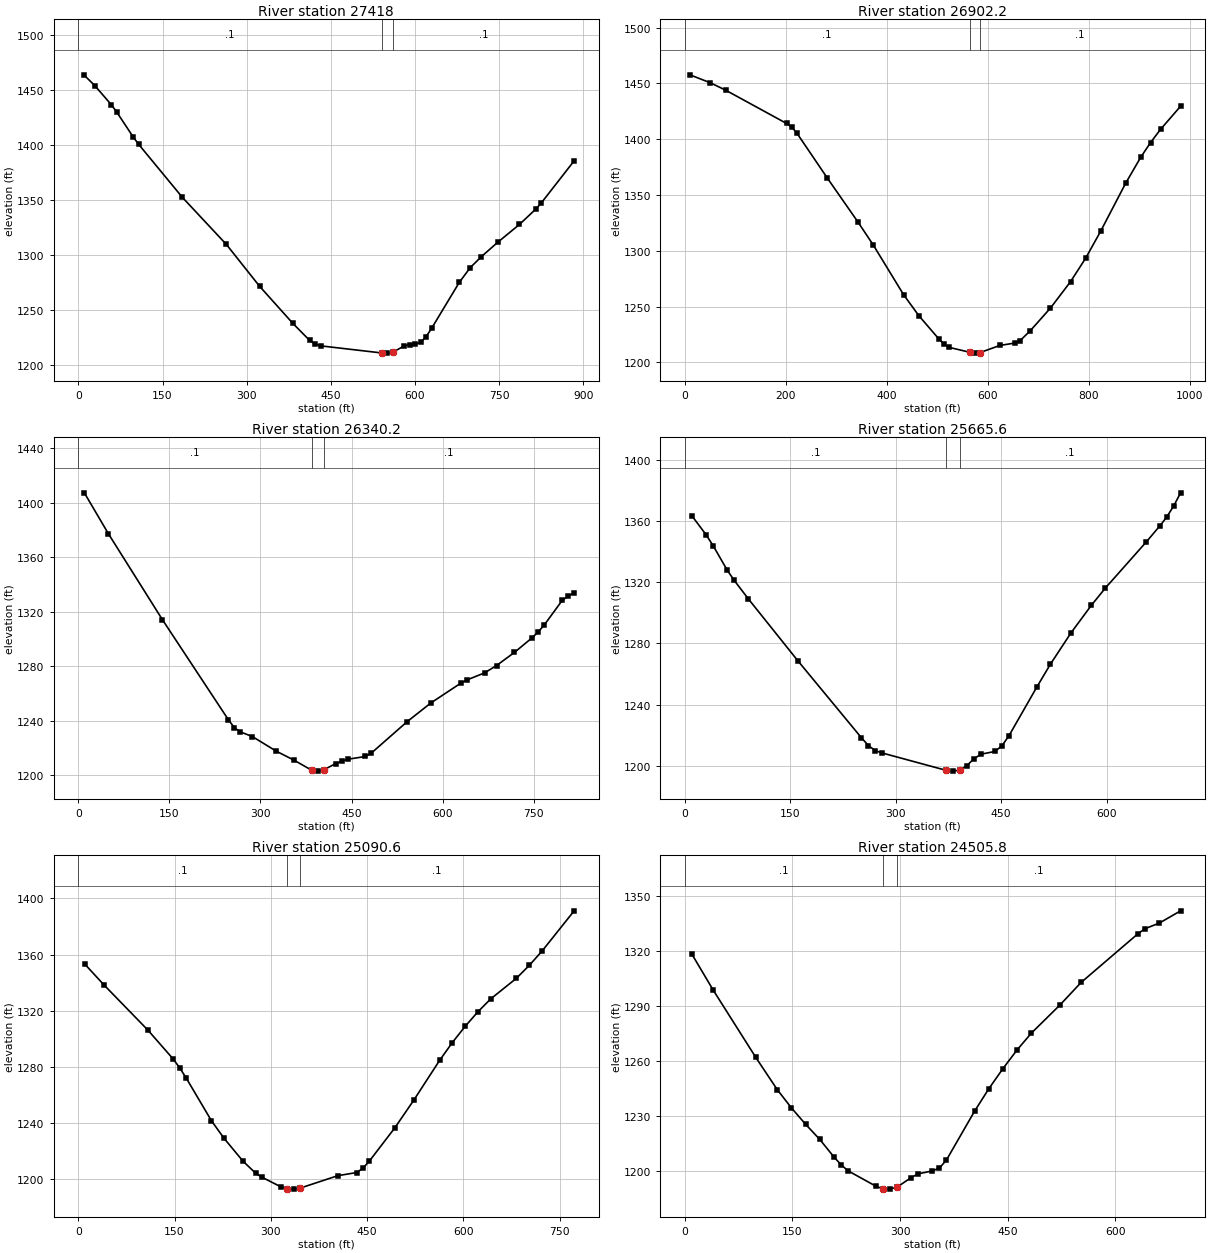
Type RM Length L Ch R = 1 ,27418   ,515,515.9,517.2
XS GIS Cut Line= 4
      1711511.42      149913.009     1711784.607       149898.63
     1712158.442       149859.09     1712388.494      149815.955
#Sta/Elev= 30
     9.8 1463.42    29.3 1453.63    58.6 1436.42    68.4 1429.64    97.7  1407.1
   107.5 1400.34   185.6 1352.13   263.8 1309.54     323 1271.57   382.4 1237.84
   412.1 1222.52     422 1219.13   431.8 1217.54   540.6 1211.09   550.6 1210.94
   560.6 1211.89   580.2 1217.28   590.1 1218.73     600 1218.98   609.9 1220.64
   619.8 1225.95   629.7  1233.6   678.7 1275.03   698.2 1288.42   717.8  1298.3
     747 1311.35     786 1327.68   815.3 1341.69     825 1347.22   883.5 1385.43
#Mann= 3 , 0 , 0
       0      .1       0   540.6    .045       0   560.6      .1       0
Bank Sta=540.6,560.6
XS Rating Curve= 0 ,0
Exp/Cntr=0.3,0.1

Type RM Length L Ch R = 1 ,26902.2 ,568.6,562,554.8
XS GIS Cut Line= 4
     1711421.556      150380.302     1711834.931      150373.113
      1712126.09      150365.924     1712402.872      150344.357
#Sta/Elev= 30
    10.1 1457.77    50.4 1450.67    80.7 1444.08   201.7 1414.17   211.8 1410.92
   221.8  1405.7   282.3  1365.3   342.9 1325.97   373.1 1305.47   433.5 1260.71
   463.7  1241.9   503.8 1220.82   513.9 1216.35   523.9 1213.52   564.1 1209.18
   574.1 1208.37   584.1 1208.76   624.3 1215.26   654.5 1217.45   664.5 1219.65
   684.6 1228.51   724.5 1248.79   764.2 1272.43   793.9 1293.25   823.7 1317.47
   873.2 1360.46     903  1383.7   922.8 1397.11   942.6 1408.96   982.3 1429.67
#Mann= 3 , 0 , 0
       0      .1       0   564.1    .045       0   584.1      .1       0
Bank Sta=564.1,584.1
XS Rating Curve= 0 ,0
Exp/Cntr=0.3,0.1

Type RM Length L Ch R = 1 ,26340.2 ,666,674.6,682.5
XS GIS Cut Line= 4
     1711692.945      151120.783     1711912.214      150951.838
     1712138.671      150858.379     1712422.642      150779.299
#Sta/Elev= 30
     9.9 1407.12    49.4 1377.22   138.4 1314.22   247.1 1240.86     257 1235.01
   266.9 1231.93   286.6 1228.54   325.8 1217.86   355.2 1211.23   384.4 1203.85
   394.4  1203.2   404.4 1204.22   423.8  1208.7   433.6 1210.42   443.4 1211.87
   472.8 1213.92   482.6 1216.43   541.4  1239.4   580.7 1253.18   629.9 1267.65
   639.7 1269.95   669.2 1275.22   688.8 1280.58   718.3 1290.21   747.8 1301.08
   757.6 1305.32   767.4 1310.32   796.9 1328.27   806.7 1331.52   816.6 1333.79
#Mann= 3 , 0 , 0
       0      .1       0   384.4    .045       0   404.4      .1       0
Bank Sta=384.4,404.4
XS Rating Curve= 0 ,0
Exp/Cntr=0.3,0.1

Type RM Length L Ch R = 1 ,25665.6 ,584.4,575,566.4
XS GIS Cut Line= 4
     1712020.051      151429.915     1712260.887      151419.132
     1712490.939      151422.726     1712724.586      151408.348
#Sta/Elev= 30
      10 1363.41    30.1 1351.07    40.2 1343.91    60.3 1327.86    70.3 1321.14
    90.4 1309.07   160.7  1268.7   251.1 1218.42   261.1 1213.27   271.1 1209.89
   281.1 1208.36   371.1 1197.15   381.1 1196.56   391.1 1197.17   401.1 1200.16
   411.1 1204.54   421.1 1207.61   441.1  1209.4   451.2 1213.16   461.2 1219.81
   500.4 1251.26   519.9 1266.35   549.2 1286.84   578.4 1304.98     598 1316.08
   656.5 1346.36     676 1356.96   685.7 1362.71   695.5 1369.93   705.2 1378.36
#Mann= 3 , 0 , 0
       0      .1       0   371.1    .045       0   391.1      .1       0
Bank Sta=371.1,391.1
XS Rating Curve= 0 ,0
Exp/Cntr=0.3,0.1

Type RM Length L Ch R = 1 ,25090.6 ,589.5,584.8,585.5
XS GIS Cut Line= 4
     1712138.671       152134.45     1712321.994      152037.397
     1712566.425      151933.155     1712825.234      151782.183
#Sta/Elev= 30
     9.9 1353.32    39.5 1338.62   108.7 1306.06   148.2  1285.4     158 1279.27
   167.9 1272.22   207.4 1241.66   227.1 1229.08   256.6 1212.83   276.3 1204.23
   286.2 1201.37   315.7 1194.51   325.4 1193.13   335.4 1192.88   345.4 1193.55
   404.3 1202.45   433.8  1204.7   443.6 1207.75   453.5  1212.8   493.1 1236.43
   523.1 1256.46     563 1284.56     583 1297.36     603 1308.93     623 1319.35
   642.9  1328.5   682.9 1343.17   702.9 1352.34   722.8 1362.55   772.8  1391.2
#Mann= 3 , 0 , 0
       0      .1       0   325.4    .045       0   345.4      .1       0
Bank Sta=325.4,345.4
XS Rating Curve= 0 ,0
Exp/Cntr=0.3,0.1

Type RM Length L Ch R = 1 ,24505.8 ,319.6,322.9,326.1
XS GIS Cut Line= 4
     1712530.479      152594.555     1712695.829      152504.691
     1712868.368      152375.286     1713112.799      152224.315
#Sta/Elev= 30
     9.9 1318.35    39.6 1298.79      99 1262.09   128.8  1244.6   148.6 1234.62
   168.4 1225.67   188.2  1217.4   207.8 1207.91   217.6 1203.75   227.4 1200.36
   266.6 1191.89   276.2  1190.5   286.2 1190.34   296.2 1191.52   315.6 1196.63
   325.4 1198.69     345 1200.24   354.8 1201.78   364.7 1206.17   403.9 1232.77
   423.7 1244.97   443.5 1256.02   463.3 1266.23   483.1 1275.33   522.7 1290.56
   552.5 1302.96   631.7 1329.49   641.6 1332.25   661.4 1335.28   691.2 1341.98
#Mann= 3 , 0 , 0
       0      .1       0   276.2    .045       0   296.2      .1       0
Bank Sta=276.2,296.2
XS Rating Curve= 0 ,0
Exp/Cntr=0.3,0.1

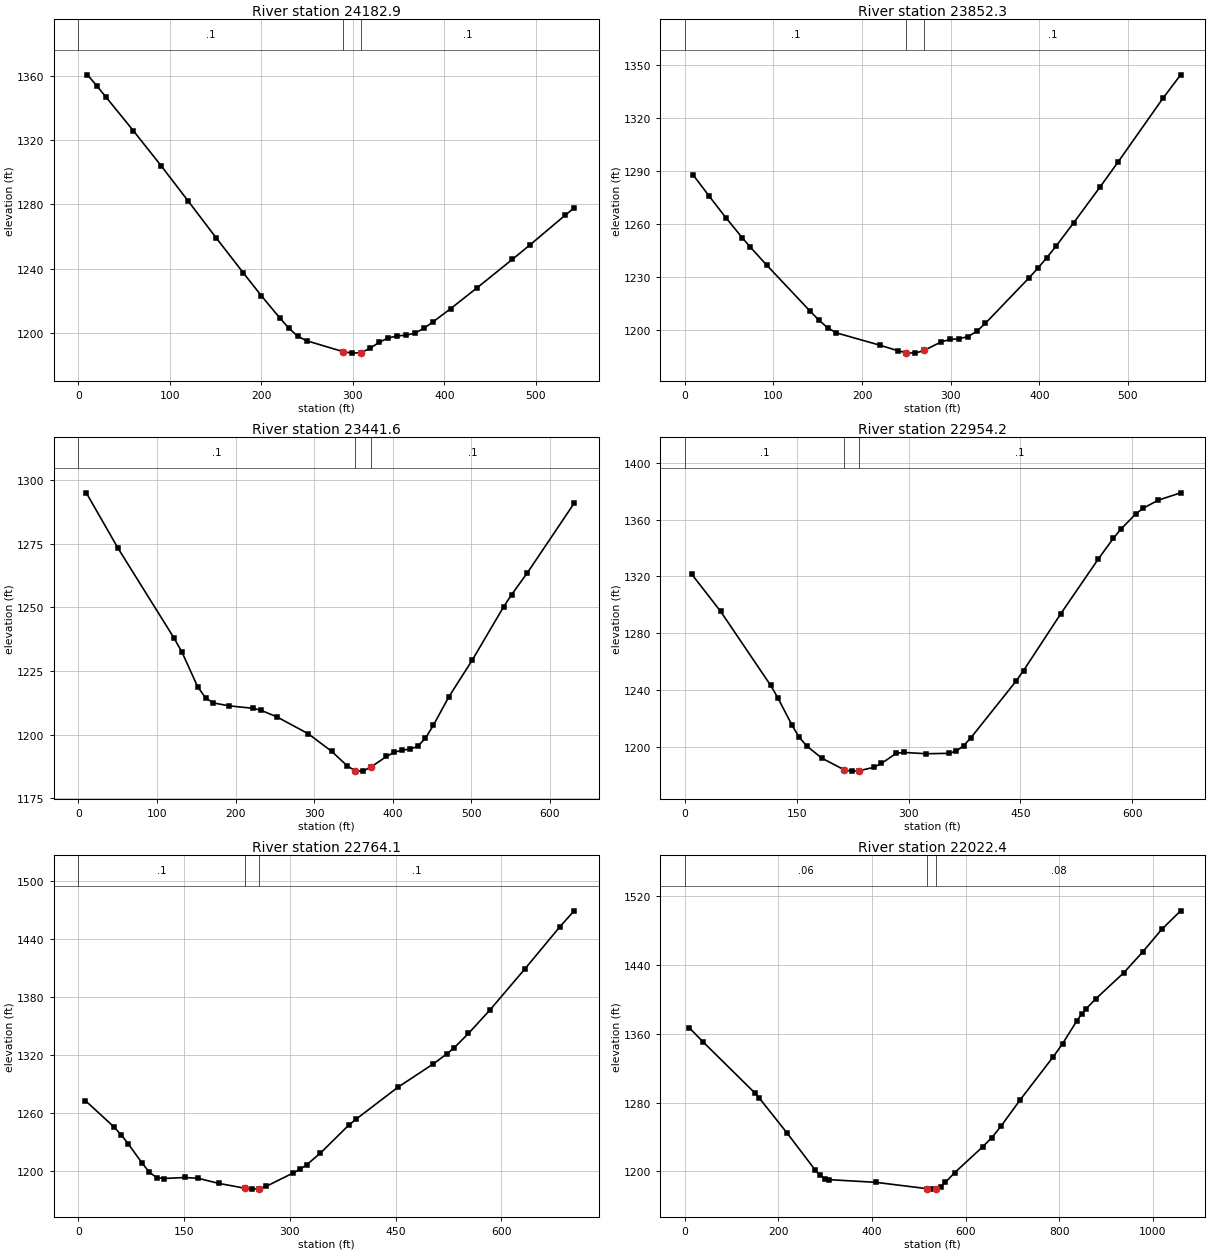
Type RM Length L Ch R = 1 ,24182.9 ,326.6,330.7,334.6
XS GIS Cut Line= 4
     1712685.392      152813.604     1712847.148      152759.686
      1713030.47      152662.633     1713159.875      152561.985
#Sta/Elev= 30
      10 1360.49    20.1 1353.69    30.1 1346.76    60.2 1325.69    90.3 1304.09
   120.4 1281.77   150.4 1259.31   180.4 1237.31   200.1  1223.1   219.9 1209.54
   229.8 1203.18   239.6    1198   249.5 1195.18   288.9 1188.48   298.9 1187.48
   308.9 1187.77   318.7  1190.4   328.5 1194.11   338.4 1196.87   348.3 1198.14
   358.2 1198.65   368.1 1199.96   377.9 1202.97   387.6 1206.87   406.9 1215.12
   435.8  1228.1   474.4 1245.78   493.7 1254.79   532.2 1273.27   541.9 1277.74
#Mann= 3 , 0 , 0
       0      .1       0   288.9    .045       0   308.9      .1       0
Bank Sta=288.9,308.9
XS Rating Curve= 0 ,0
Exp/Cntr=0.3,0.1

Type RM Length L Ch R = 1 ,23852.3 ,408,410.7,413.4
XS GIS Cut Line= 4
      1712885.21      153032.946     1712985.858      153018.568
     1713269.828      152932.298     1713417.206      152867.596
#Sta/Elev= 30
     9.2 1288.07    27.7 1275.74    46.2 1263.74    64.7 1252.35    73.9 1246.97
    92.4 1236.76   141.2 1210.73   151.1 1205.65     161 1201.26   170.9 1198.34
   220.4 1191.28   240.2 1188.22     250    1187     260 1186.83     270 1188.36
   289.6 1193.29   299.5 1194.56   309.4 1195.03   319.3 1196.14   329.2 1199.13
   339.1 1203.72   388.6 1229.66   398.5  1235.1   408.5 1241.03   418.6 1247.34
   438.7 1260.74   468.9 1281.33     489 1295.35   539.3 1331.28   559.4 1344.68
#Mann= 3 , 0 , 0
       0      .1       0     250    .045       0     270      .1       0
Bank Sta=250,270
XS Rating Curve= 0 ,0
Exp/Cntr=0.3,0.1

Type RM Length L Ch R = 1 ,23441.6 ,525.8,487.4,448.9
XS GIS Cut Line= 4
     1713004.962      153597.439     1713130.772       153378.17
     1713346.446      153342.225     1713421.932      153202.037
#Sta/Elev= 30
    10.1 1295.03    50.6  1273.2   121.3 1238.16   131.5 1232.63   151.7 1218.89
   161.8 1214.43   171.9 1212.45   192.1  1211.3   222.5 1210.34   232.6 1209.54
   252.8 1206.95   292.6 1200.32   322.4 1193.39   342.2  1187.7   352.1 1185.79
   362.1 1185.66   372.1 1187.24   391.9 1191.42   401.9 1193.02   411.8 1193.93
   421.8 1194.29   431.7 1195.41   441.6 1198.63   451.6 1203.67   471.4 1214.91
   501.3  1229.4   541.1 1250.32   551.1 1255.01     571 1263.51   630.7 1290.93
#Mann= 3 , 0 , 0
       0      .1       0   352.1    .045       0   372.1      .1       0
Bank Sta=352.1,372.1
XS Rating Curve= 0 ,0
Exp/Cntr=0.3,0.1

Type RM Length L Ch R = 1 ,22954.2 ,194.4,190.1,185.7
XS GIS Cut Line= 4
     1713614.681      153753.363     1713626.413      153600.351
     1713542.789      153440.635     1713524.817      153109.935
#Sta/Elev= 30
     9.6 1321.37      48 1295.47   115.1 1243.46   124.7 1234.74   143.9 1215.32
   153.5 1206.91   163.5 1200.85   183.5 1192.39   213.6 1184.09   223.6 1183.17
   233.6  1183.4   253.6 1185.89   263.6 1188.57   283.7 1195.72   293.7 1196.31
   323.7 1195.39   353.8 1195.68   363.9  1197.2   373.9    1201   383.9 1206.77
   444.1 1246.35   454.2 1253.81   504.4 1293.95   554.5 1332.25   574.6 1346.72
   584.6 1353.15   604.7 1363.91   614.8 1367.97   634.8 1373.57   664.9 1378.76
#Mann= 3 , 0 , 0
       0      .1       0   213.6    .045       0   233.6      .1       0
Bank Sta=213.6,233.6
XS Rating Curve= 0 ,0
Exp/Cntr=0.3,0.1

Type RM Length L Ch R = 1 ,22764.1 ,722.2,741.7,761.2
XS GIS Cut Line= 4
     1713824.523      153593.844     1713767.038      153464.934
     1713644.642      153316.496     1713634.011      152946.822
#Sta/Elev= 30
    10.1 1272.58    50.4 1245.56    60.5 1237.42    70.6 1228.16    90.7 1207.76
   100.8 1198.63   110.9 1193.04     121 1192.06   150.8 1193.11     170 1192.26
   198.9 1187.07     237  1181.9     247 1181.07     257 1181.69   266.2 1183.83
   304.7  1197.8   314.3 1201.44   323.9 1206.25   343.5 1218.39   383.5 1247.23
   393.5 1253.17   453.5 1286.58   503.5 1310.63   523.4 1321.39   533.4 1327.57
   553.4 1342.15   583.4 1366.05   633.4 1408.89   683.4 1452.85   703.4 1469.12
#Mann= 3 , 0 , 0
       0      .1       0     237    .045       0     257      .1       0
Bank Sta=237,257
XS Rating Curve= 0 ,0
Exp/Cntr=0.3,0.1

Type RM Length L Ch R = 1 ,22022.4 ,552.5,568.2,583.8
XS GIS Cut Line= 4
     1714216.331      153586.655     1714299.006      153237.982
     1714378.086      152961.201     1714381.681      152547.826
#Sta/Elev= 30
      10 1366.82    39.8 1350.22   149.3 1291.45   159.3 1285.24     219 1244.29
   278.7 1201.51   288.7 1195.38   298.6 1191.68   308.6 1190.33     408 1187.25
   517.1  1179.9   527.1 1179.32   537.1 1179.72   546.9 1182.24   556.9  1187.2
   576.7 1198.47   636.3 1228.41   656.3 1239.34   676.4 1253.06   716.8 1283.31
   787.4 1333.37   807.5 1348.67   837.8 1375.21   847.9 1382.87   857.9  1389.3
   878.1 1400.67   938.6 1431.39   978.9 1455.57  1019.3 1481.68  1059.6 1503.19
#Mann= 3 , 0 , 0
       0     .06       0   517.1    .045       0   537.1     .08       0
Bank Sta=517.1,537.1
XS Rating Curve= 0 ,0
Exp/Cntr=0.3,0.1

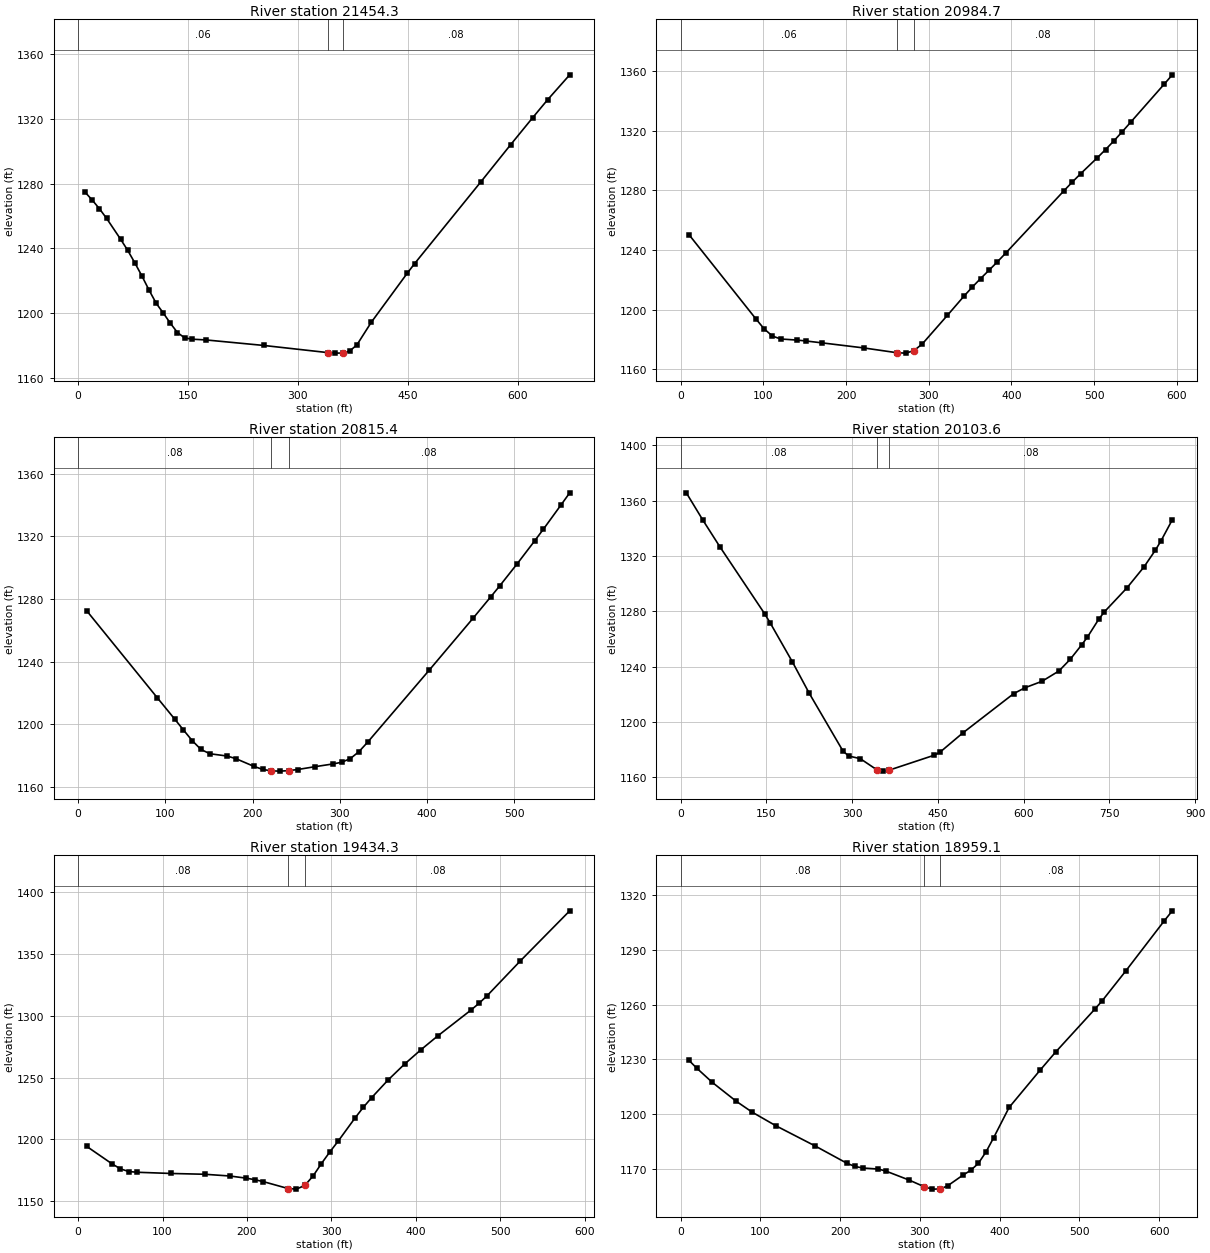
Type RM Length L Ch R = 1 ,21454.3 ,461.4,469.6,477.8
XS GIS Cut Line= 4
     1714503.896      153615.412     1714575.787      153500.386
     1714852.569      153353.008     1715053.865       153259.55
#Sta/Elev= 30
     9.7 1274.65    19.4 1269.78    29.1  1264.5    38.8 1258.59    58.1 1245.57
    67.8 1238.68    77.5 1230.95    87.2 1222.81    96.9 1214.11   106.6    1206
   116.3 1199.95     126 1193.61   135.6 1187.92   145.4  1184.6   155.2  1183.8
   174.8 1183.31   253.2 1179.92   341.2 1175.47   351.2 1175.16   361.2 1175.23
   370.8 1176.47   380.6 1180.23   400.2  1194.2   449.2 1224.48   459.3 1230.49
   550.1 1281.25   590.4 1304.04   620.7 1320.87   640.9 1331.86   671.2 1347.35
#Mann= 3 , 0 , 0
       0     .06       0   341.2    .045       0   361.2     .08       0
Bank Sta=341.2,361.2
XS Rating Curve= 0 ,0
Exp/Cntr=0.3,0.1

Type RM Length L Ch R = 1 ,20984.7 ,164.7,169.2,173.7
XS GIS Cut Line= 2
     1714626.111       153874.22     1715219.215      153831.086
#Sta/Elev= 30
    10.1 1250.25    90.7 1193.93   100.8 1187.16   110.9 1182.25   120.9 1180.28
   141.1 1179.52   151.2 1178.95   171.3 1177.65   221.7 1174.25   262.1 1171.01
   272.1 1170.78   282.1 1172.41   292.3 1176.97   322.5 1196.07   342.7 1209.05
   352.8 1215.15   362.8 1220.86   372.9 1226.38     383 1232.02   393.1 1237.89
   463.6 1279.77   473.7 1285.63   483.8 1291.23     504 1301.96     514 1307.49
   524.1 1313.31   534.2 1319.46   544.3 1325.79   584.6 1351.17   594.7 1357.63
#Mann= 3 , 0 , 0
       0     .06       0   262.1    .045       0   282.1     .08       0
Bank Sta=262.1,282.1
XS Rating Curve= 0 ,0
Exp/Cntr=0.3,0.1

Type RM Length L Ch R = 1 ,20815.4 ,740.2,711.9,683.3
XS GIS Cut Line= 2
     1714626.111      154043.165     1715186.864      153989.247
#Sta/Elev= 30
    10.1 1272.31    90.5 1217.08   110.7 1203.28   120.7 1196.35   130.8 1189.49
   140.8 1183.91   150.9 1181.18     171 1179.69   181.1 1177.96   201.2 1173.17
   211.3 1171.19   221.4 1170.22   231.4 1170.07   241.4 1170.39   251.5 1171.09
   271.6 1172.92   291.7 1174.63   301.8  1175.7   311.8 1178.02   321.9 1182.56
     332 1188.71   402.4 1234.61   452.7 1267.84   472.8 1281.37   482.9 1288.26
     503 1302.42   523.1 1317.12   533.2 1324.65   553.3 1340.07   563.3 1347.83
#Mann= 3 , 0 , 0
       0     .08       0   221.4    .045       0   241.4     .08       0
Bank Sta=221.4,241.4
XS Rating Curve= 0 ,0
Exp/Cntr=0.3,0.1

Type RM Length L Ch R = 1 ,20103.6 ,645.5,669.3,693
XS GIS Cut Line= 4
     1714913.676      154895.077     1715093.405      154715.349
     1715179.674      154492.486      1715420.51      154215.704
#Sta/Elev= 30
     9.8 1365.72    39.1 1345.77    68.4 1326.81   146.6 1278.46   156.4 1271.79
   195.5 1243.42   224.8 1220.85     284 1178.98     294 1175.43   313.9 1173.61
   343.7 1165.35   353.7 1164.54   363.7 1165.11   443.4 1176.03   453.3 1178.12
   493.2 1192.04   582.4 1220.52   602.2 1224.81     632 1229.46   661.7 1236.94
   681.6 1245.45   701.4 1255.79   711.3  1261.3   731.1  1274.2   741.1 1279.65
   780.7 1297.02   810.5 1312.18   830.3  1324.2   840.2 1330.98     860 1346.24
#Mann= 3 , 0 , 0
       0     .08       0   343.7    .045       0   363.7     .08       0
Bank Sta=343.7,363.7
XS Rating Curve= 0 ,0
Exp/Cntr=0.3,0.1

Type RM Length L Ch R = 1 ,19434.3 ,464.6,475.2,485.8
XS GIS Cut Line= 4
     1715460.051      154920.239      1715585.86      154859.132
     1715783.561      154851.942     1716027.992      154844.753
#Sta/Elev= 30
      10 1194.44      40 1180.29      50  1176.2    59.9    1174    69.9  1173.4
   109.9 1172.43   149.8 1171.78   179.4 1170.39   199.2 1168.62   209.1 1167.38
     219 1165.88   248.6 1160.23   258.6 1159.74   268.6 1162.82   278.3 1170.43
   288.2 1180.49   298.1 1189.85     308 1198.63   327.8 1217.23   337.7 1225.96
   347.5 1233.74     367 1248.07   386.6    1261   406.2 1272.75   425.7 1283.71
   464.9 1304.57   474.6 1310.12   484.4  1316.4   523.5 1344.42   582.2 1385.15
#Mann= 3 , 0 , 0
       0     .08       0   248.6    .045       0   268.6     .08       0
Bank Sta=248.6,268.6
XS Rating Curve= 0 ,0
Exp/Cntr=0.3,0.1

Type RM Length L Ch R = 1 ,18959.1 ,357.7,329.7,301.1
XS GIS Cut Line= 4
      1715301.89      155175.453     1715510.374      155268.912
      1715672.13      155355.182     1715848.264      155250.939
#Sta/Elev= 30
     9.9 1229.71    19.9 1225.33    39.7 1217.44    69.5 1207.19    89.4 1201.25
   119.2 1193.79   168.9 1182.64   208.6 1173.21   218.5  1171.5   228.5 1170.66
   247.8 1170.08   257.4 1168.96   286.4 1164.08   305.3 1160.44   315.3 1159.11
   325.3 1159.19   334.6 1160.88   353.9 1166.75   363.6 1169.35   373.2 1173.15
   382.9 1179.47   392.5 1187.25   411.8 1203.74   450.8 1224.19   470.3 1234.11
     519 1257.34   528.8  1262.2     558  1278.3   606.7 1305.95   616.5 1311.26
#Mann= 3 , 0 , 0
       0     .08       0   305.3    .045       0   325.3     .08       0
Bank Sta=305.3,325.3
XS Rating Curve= 0 ,0
Exp/Cntr=0.3,0.1

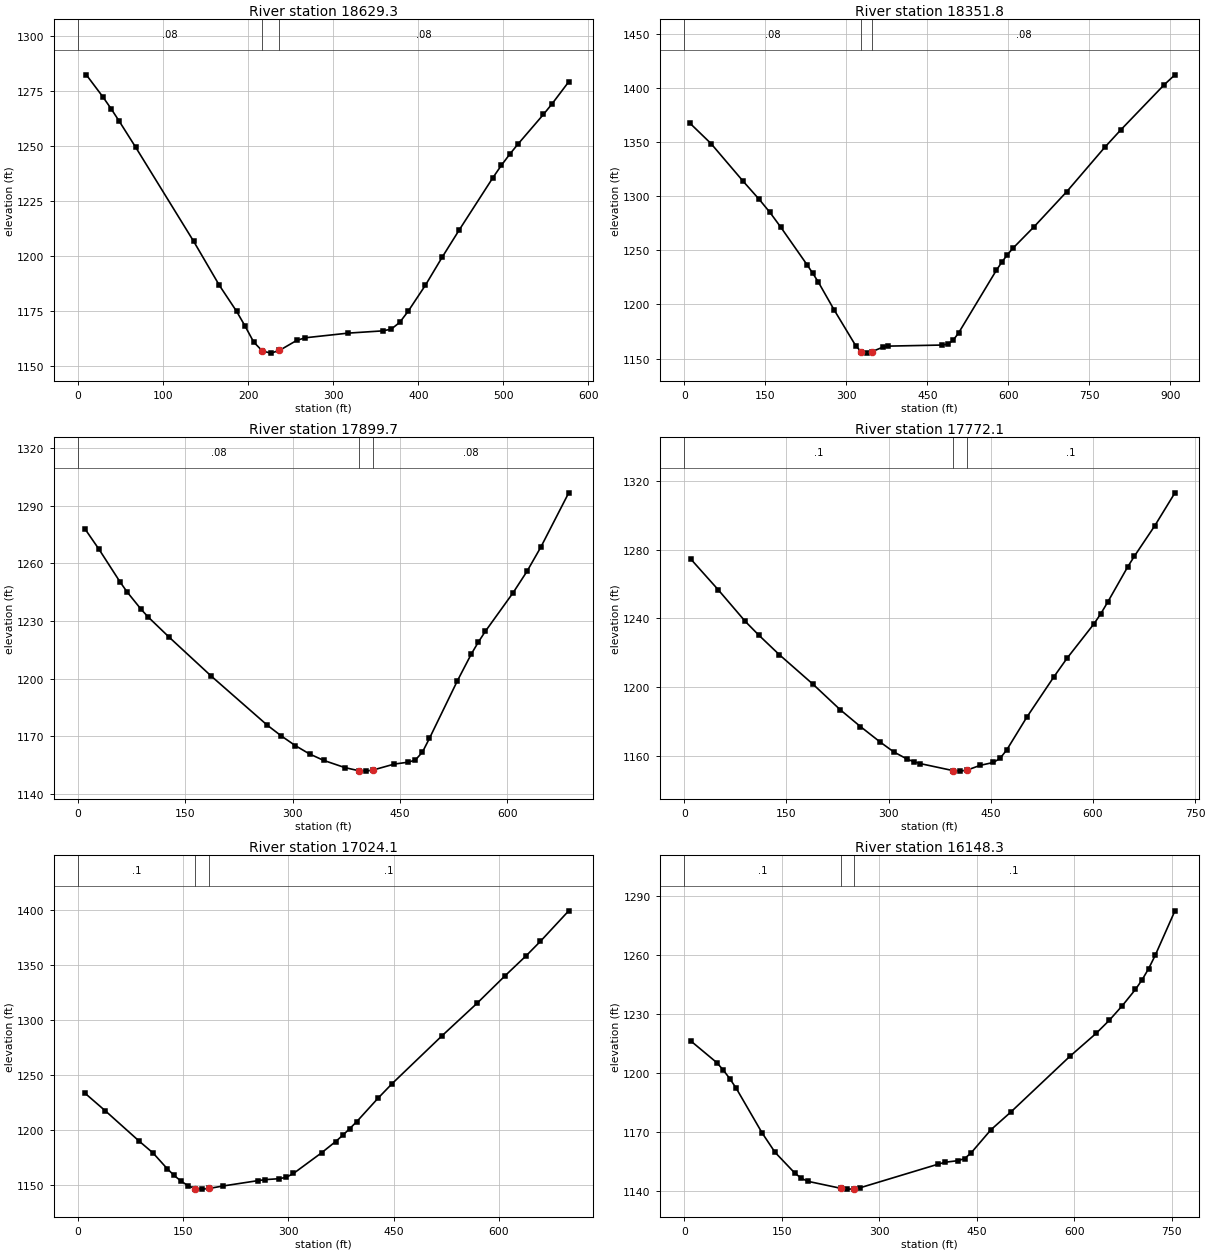
Type RM Length L Ch R = 1 ,18629.3 ,289.8,277.5,265.3
XS GIS Cut Line= 4
     1715431.294      155754.179     1715539.131      155671.503
     1715718.859      155466.613     1715826.696      155337.209
#Sta/Elev= 30
     9.7 1282.49    29.1  1272.5    38.8 1267.09    48.5 1261.33    67.9 1249.44
   135.9 1206.76   166.2 1186.69   186.4 1174.92   196.4 1168.17   206.5 1160.95
   216.7 1156.87   226.7 1155.91   236.7 1157.12     257 1161.68   267.1 1162.89
   317.6 1165.01     358 1166.03   368.1 1166.79   378.1 1169.86   388.2    1175
   408.4  1186.8   428.2  1199.6   448.1  1211.9   487.7 1235.68   497.6 1241.26
   507.5 1246.36   517.4 1251.06   547.2 1264.49   557.1 1269.19   576.9 1279.32
#Mann= 3 , 0 , 0
       0     .08       0   216.7    .045       0   236.7     .08       0
Bank Sta=216.7,236.7
XS Rating Curve= 0 ,0
Exp/Cntr=0.3,0.1

Type RM Length L Ch R = 1 ,18351.8 ,454.2,452.1,450
XS GIS Cut Line= 4
     1715740.427      155984.231     1715855.453      155764.962
     1715902.182      155437.857     1716071.127      155153.886
#Sta/Elev= 30
     9.9 1367.76    49.5 1348.66   108.9 1313.88   138.7 1297.11   158.5 1285.12
   178.3 1271.64   227.8 1236.33   237.7 1228.93   247.6 1221.14   277.6 1194.82
   317.7 1161.59   327.7 1156.15   337.7 1154.97   347.7 1156.37   367.8 1160.52
   377.8 1161.45   477.9 1162.45   487.9 1163.34   497.9  1166.9   507.9 1173.63
     578 1231.68     588 1239.09   598.1 1245.84   608.1  1251.7   648.1 1272.01
   708.2 1304.23   778.3 1345.07   808.3 1361.37   888.4 1402.93   908.5 1412.21
#Mann= 3 , 0 , 0
       0     .08       0   327.7    .045       0   347.7     .08       0
Bank Sta=327.7,347.7
XS Rating Curve= 0 ,0
Exp/Cntr=0.3,0.1

Type RM Length L Ch R = 1 ,17899.7 ,129.2,127.6,126
XS GIS Cut Line= 4
     1716285.267      156009.205      1716293.08      155725.351
     1716300.892      155498.788     1716313.913      155324.309
#Sta/Elev= 30
     9.8 1277.84    29.4 1267.24    58.8 1250.26    68.5 1245.14    88.1 1236.09
    97.9 1232.11   127.3 1221.59     186 1201.38   264.4 1175.81     284 1170.23
   303.7 1165.16   323.4 1160.86   343.1 1157.52   372.7 1153.77   392.2 1152.13
   402.2 1151.92   412.2 1152.49   441.7 1155.58   461.4 1156.58   471.2 1157.67
   481.1 1161.76   490.9 1168.91   530.1 1198.96   549.5 1212.86   559.3 1219.04
     569  1224.6   607.9 1244.73   627.3 1255.86   646.7  1268.5   685.6  1296.7
#Mann= 3 , 0 , 0
       0     .08       0   392.2    .045       0   412.2     .08       0
Bank Sta=392.2,412.2
XS Rating Curve= 0 ,0
Exp/Cntr=0.3,0.1

Type RM Length L Ch R = 1 ,17772.1 ,768.4,748,727.7
XS GIS Cut Line= 4
     1716403.624      156016.582     1716425.192      155768.557
     1716414.408       155495.37     1716403.624      155297.669
#Sta/Elev= 30
      10 1274.29    49.8 1256.62    89.6 1238.17   109.5 1230.16   139.4 1218.87
   189.2 1201.53     229 1186.74   258.7 1176.94     288 1167.83   307.5 1162.21
   327.1 1158.04   336.8  1156.5   346.6 1155.38   395.2 1151.26   405.2 1151.01
   415.2 1151.61   434.5 1154.38     454 1156.07   463.8 1158.52   473.5  1163.4
   502.8 1182.35   542.2 1205.65     562 1216.75   601.6 1236.81   611.5 1242.63
   621.4 1249.23   651.1 1269.98     661 1276.24   690.7 1293.81   720.4 1313.06
#Mann= 3 , 0 , 0
       0      .1       0   395.2    .045       0   415.2      .1       0
Bank Sta=395.2,415.2
XS Rating Curve= 0 ,0
Exp/Cntr=0.3,0.1

Type RM Length L Ch R = 1 ,17024.1 ,855.3,875.8,896.2
XS GIS Cut Line= 4
     1717133.321      155635.558     1717097.375       155534.91
     1716892.485      155391.127      1716730.73      155089.184
#Sta/Elev= 30
     9.7 1233.26    38.9 1217.13    87.4 1189.41   106.9 1178.79   126.9 1164.63
   136.9 1158.36   146.9 1153.16   156.9 1148.92     167 1146.44     177 1145.88
     187 1146.51     207 1148.77   257.1 1153.67   267.1 1154.54   287.1 1155.39
   297.1 1156.72   307.1 1160.11   347.2 1178.93   367.3 1189.19   377.3 1194.81
   387.4 1200.95   397.5 1207.39   427.7  1228.6   447.9 1241.94   518.4  1285.1
   568.8 1314.95     609 1340.13   639.3 1358.49   659.4 1371.49   699.7  1399.2
#Mann= 3 , 0 , 0
       0      .1       0     167    .045       0     187      .1       0
Bank Sta=167,187
XS Rating Curve= 0 ,0
Exp/Cntr=0.3,0.1

Type RM Length L Ch R = 1 ,16148.3 ,524.2,555.2,586.1
XS GIS Cut Line= 4
     1717455.752      155190.226     1717550.446      155087.509
     1717575.608      154807.133     1717510.906      154480.028
#Sta/Elev= 30
      10 1216.35    49.9 1205.39    59.9 1201.63    69.9 1197.26    79.8  1192.4
   119.7  1169.7   139.7 1159.83   169.9 1149.37   179.9 1146.72     190 1145.17
   240.3 1141.65   250.3  1141.2   260.3 1141.27   270.4 1141.89     391 1153.91
   401.1 1154.82   421.2 1155.65   431.3 1156.72   441.4 1159.66   471.7 1171.32
     502 1180.21     593 1208.52   633.4 1220.17   653.6 1226.78   673.8 1234.25
     694  1242.5   704.1 1247.31   714.2 1253.01   724.3 1259.72   754.7 1282.35
#Mann= 3 , 0 , 0
       0      .1       0   240.3    .045       0   260.3      .1       0
Bank Sta=240.3,260.3
XS Rating Curve= 0 ,0
Exp/Cntr=0.3,0.1