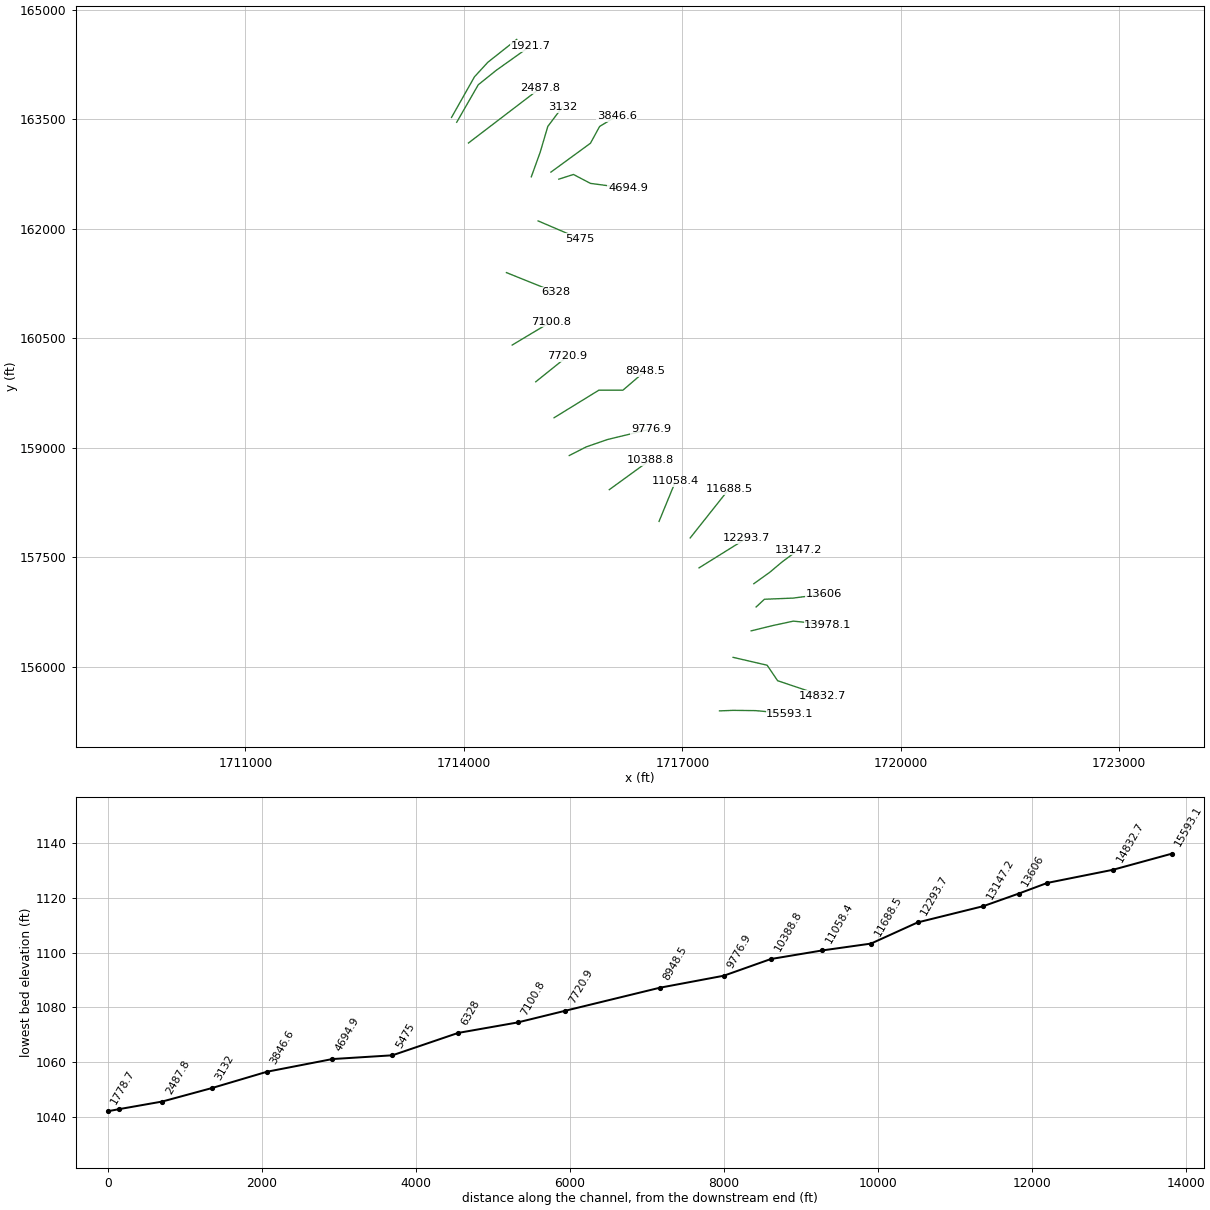
HEC-RAS study Panther Creek.prj: Panther Creek

--- Panther Creek.g01 (geometry) --- (continued)

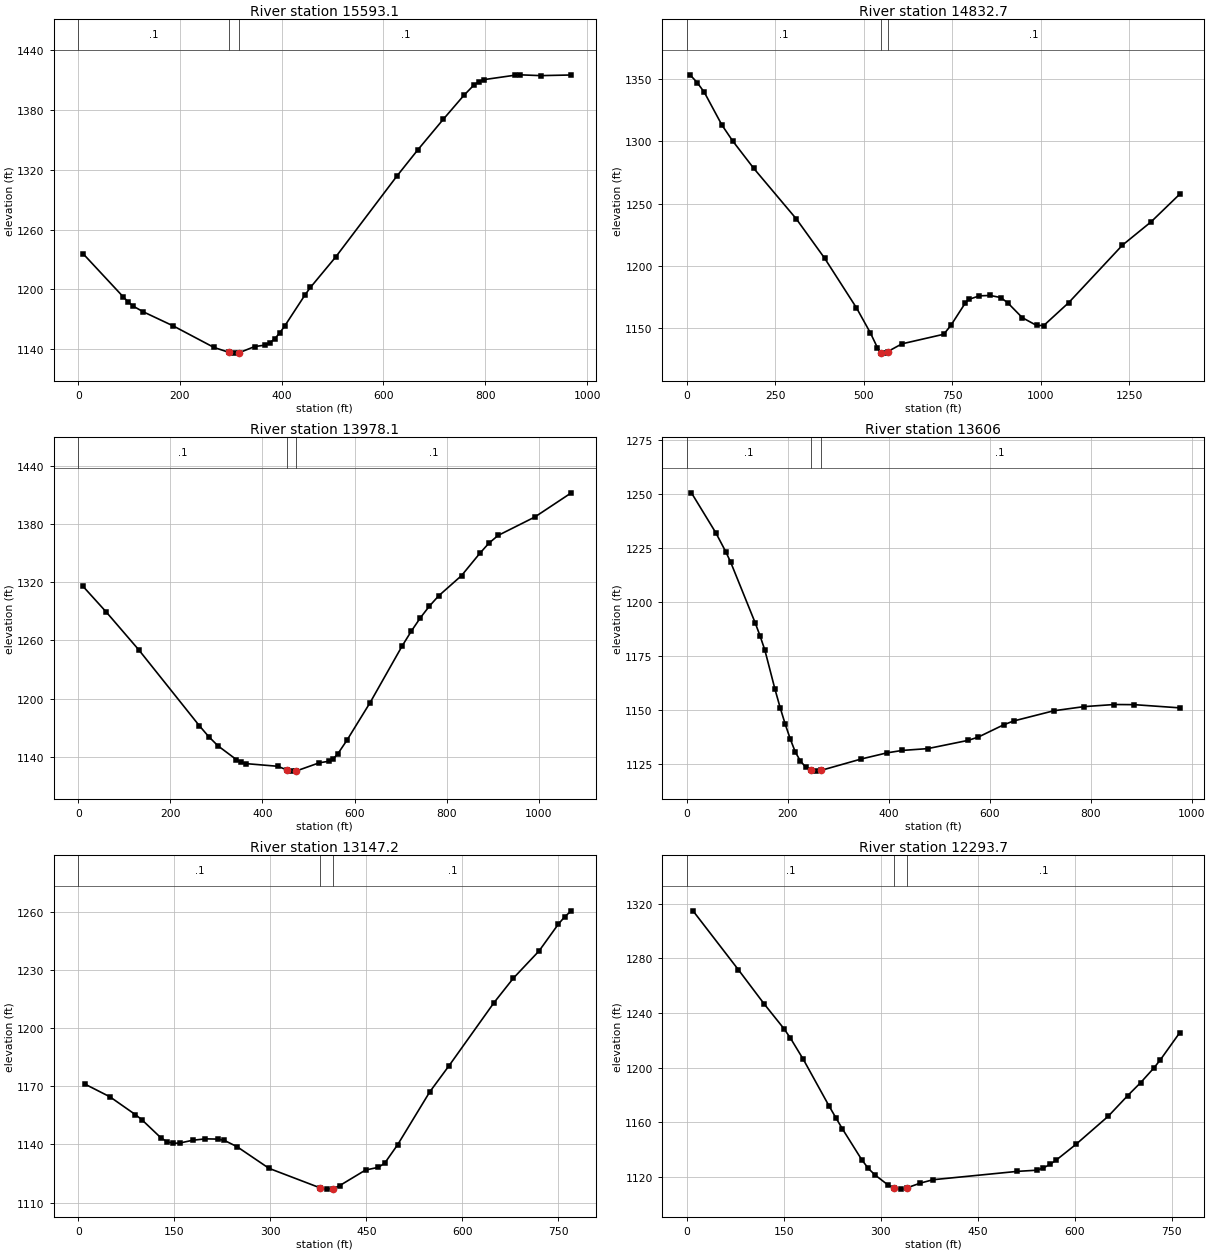
Type RM Length L Ch R = 1 ,15593.1 ,779.8,760.5,741.1
XS GIS Cut Line= 4
      1717510.75      155394.722     1717697.668      155401.911
     1718006.801      155398.316     1718477.689      155355.182
#Sta/Elev= 30
     9.8 1235.71    88.6 1192.46    98.5 1187.35   108.3 1183.12     128 1177.47
   187.1 1163.25   266.8 1141.73   296.7 1136.74   306.7 1136.02   316.7 1136.51
   346.6 1142.58   366.6 1144.03   376.5 1146.25   386.5 1150.58   396.5 1156.57
   406.5 1163.74   446.3 1194.87   456.3 1201.91   506.3 1232.69     627  1314.2
   667.2 1339.95   717.5 1370.76   757.8 1394.69   777.9 1405.26     788  1408.7
     798 1410.62   858.4 1415.03   868.5  1415.4   908.7  1414.6   969.1 1415.24
#Mann= 3 , 0 , 0
       0      .1       0   296.7    .045       0   316.7      .1       0
Bank Sta=296.7,316.7
XS Rating Curve= 0 ,0
Exp/Cntr=0.3,0.1

Type RM Length L Ch R = 1 ,14832.7 ,830.2,854.5,878.8
XS GIS Cut Line= 4
     1717697.668      156128.013     1718164.961      156020.176
     1718308.744      155808.097     1718930.604      155599.612
#Sta/Elev= 30
      10 1353.29      30 1347.09      50 1339.37    99.9 1313.02   129.9 1300.42
   189.8 1278.28   309.7 1237.83   389.7 1206.29   479.6  1166.5     519 1146.35
   538.7 1134.59   548.4 1130.54   558.4 1130.18   568.4 1131.48   607.7 1137.61
   725.9  1145.3   745.9 1152.34   786.3 1170.16   796.3 1173.24   826.6 1176.09
   856.9 1176.42   887.2 1174.71   907.3 1170.28   947.7 1158.59   988.1 1152.36
  1008.2 1152.31  1078.9 1170.73  1230.2 1216.73    1311 1235.41  1391.7 1257.55
#Mann= 3 , 0 , 0
       0      .1       0   548.4    .045       0   568.4      .1       0
Bank Sta=548.4,568.4
XS Rating Curve= 0 ,0
Exp/Cntr=0.3,0.1

Type RM Length L Ch R = 1 ,13978.1 ,375.8,372.2,368.6
XS GIS Cut Line= 4
     1717945.693      156491.065     1718240.447      156562.956
     1718524.418      156624.063     1718998.901      156577.334
#Sta/Elev= 30
    10.1 1315.93    60.7 1289.41   131.5 1250.33   262.9 1172.22   283.2 1161.01
   303.4 1151.46   343.5 1137.24   353.5 1134.45   363.5 1133.14   433.6 1130.36
   453.7 1126.47   463.7 1125.38   473.7 1125.58   523.8 1134.03   543.8 1135.48
   553.8 1137.96   563.8 1143.32   583.8 1157.44   633.6 1195.83   703.1 1254.11
     723 1269.42   742.9 1283.34   762.7 1295.48   782.6 1305.95   832.3 1326.83
     872 1349.77   891.9 1360.32   911.7 1368.19   991.2 1387.11  1070.6 1412.08
#Mann= 3 , 0 , 0
       0      .1       0   453.7    .045       0   473.7      .1       0
Bank Sta=453.7,473.7
XS Rating Curve= 0 ,0
Exp/Cntr=0.3,0.1

Type RM Length L Ch R = 1 ,13606   ,445,458.7,472.5
XS GIS Cut Line= 4
      1718013.99       156818.17     1718127.552      156923.733
     1718520.094      156939.541     1718944.982      156994.304
#Sta/Elev= 30
     9.7 1250.61    58.1 1232.02    77.5 1223.37    87.2 1218.53   135.7 1190.42
   145.4 1184.34     155  1177.7   175.2  1159.4   185.3 1150.98   195.3 1143.34
   205.4 1136.37   215.5 1130.28   225.6 1126.12   235.6 1123.43   245.8 1121.87
   255.8 1121.48   265.8 1121.79   346.4 1127.14   396.8 1129.95     427 1131.08
   477.4 1131.92   557.9 1135.77   577.8  1137.3   627.6 1142.94   647.5 1144.74
   727.2 1149.49     787 1151.41   846.8 1152.39   886.6 1152.32   976.3 1150.84
#Mann= 3 , 0 , 0
       0      .1       0   245.8    .045       0   265.8      .1       0
Bank Sta=245.8,265.8
XS Rating Curve= 0 ,0
Exp/Cntr=0.3,0.1

Type RM Length L Ch R = 1 ,13147.2 ,856.4,853.5,850.6
XS GIS Cut Line= 4
     1717982.654      157137.129     1718200.639      157292.899
     1718369.926      157434.828     1718596.041      157602.031
#Sta/Elev= 30
     9.9 1171.24    49.6 1164.57    89.3 1155.38    99.2 1152.82     129 1143.46
   138.9 1141.32   148.8  1140.6   158.8 1140.72   178.6 1142.13   198.5 1142.87
   218.3 1142.74   228.2 1142.08   248.1 1138.82     298 1127.64   378.4 1117.49
   388.4 1116.91   398.4 1117.15   408.5 1118.75   448.7 1126.76   468.8 1128.17
   478.8 1130.37   498.9 1139.85   549.1 1167.15   579.2 1180.65   649.5 1213.25
   679.7 1225.86   719.8 1239.91     750  1253.8     760 1257.61   770.1 1260.61
#Mann= 3 , 0 , 0
       0      .1       0   378.4    .045       0   398.4      .1       0
Bank Sta=378.4,398.4
XS Rating Curve= 0 ,0
Exp/Cntr=0.3,0.1

Type RM Length L Ch R = 1 ,12293.7 ,598,605.2,612.5
XS GIS Cut Line= 2
     1717230.374       157353.76     1717877.396      157756.352
#Sta/Elev= 30
      10 1314.71    80.2 1271.54   120.3 1246.34   150.4 1228.52   160.4 1221.65
   180.5 1205.94   220.6 1171.54   230.6 1163.36   240.6 1155.29   270.7 1132.55
   280.8 1126.19   290.8 1121.53   310.8 1114.22   320.9 1111.69   330.9 1110.98
   340.9 1111.96     361 1115.35     381 1117.87   511.4 1123.99   541.5 1124.84
   551.5  1126.5   561.5  1129.1   571.5 1132.32   601.6 1143.68   651.8  1164.4
   681.8 1179.47   701.9 1189.02   721.9 1199.51     732 1205.51     762 1225.41
#Mann= 3 , 0 , 0
       0      .1       0   320.9    .045       0   340.9      .1       0
Bank Sta=320.9,340.9
XS Rating Curve= 0 ,0
Exp/Cntr=0.3,0.1

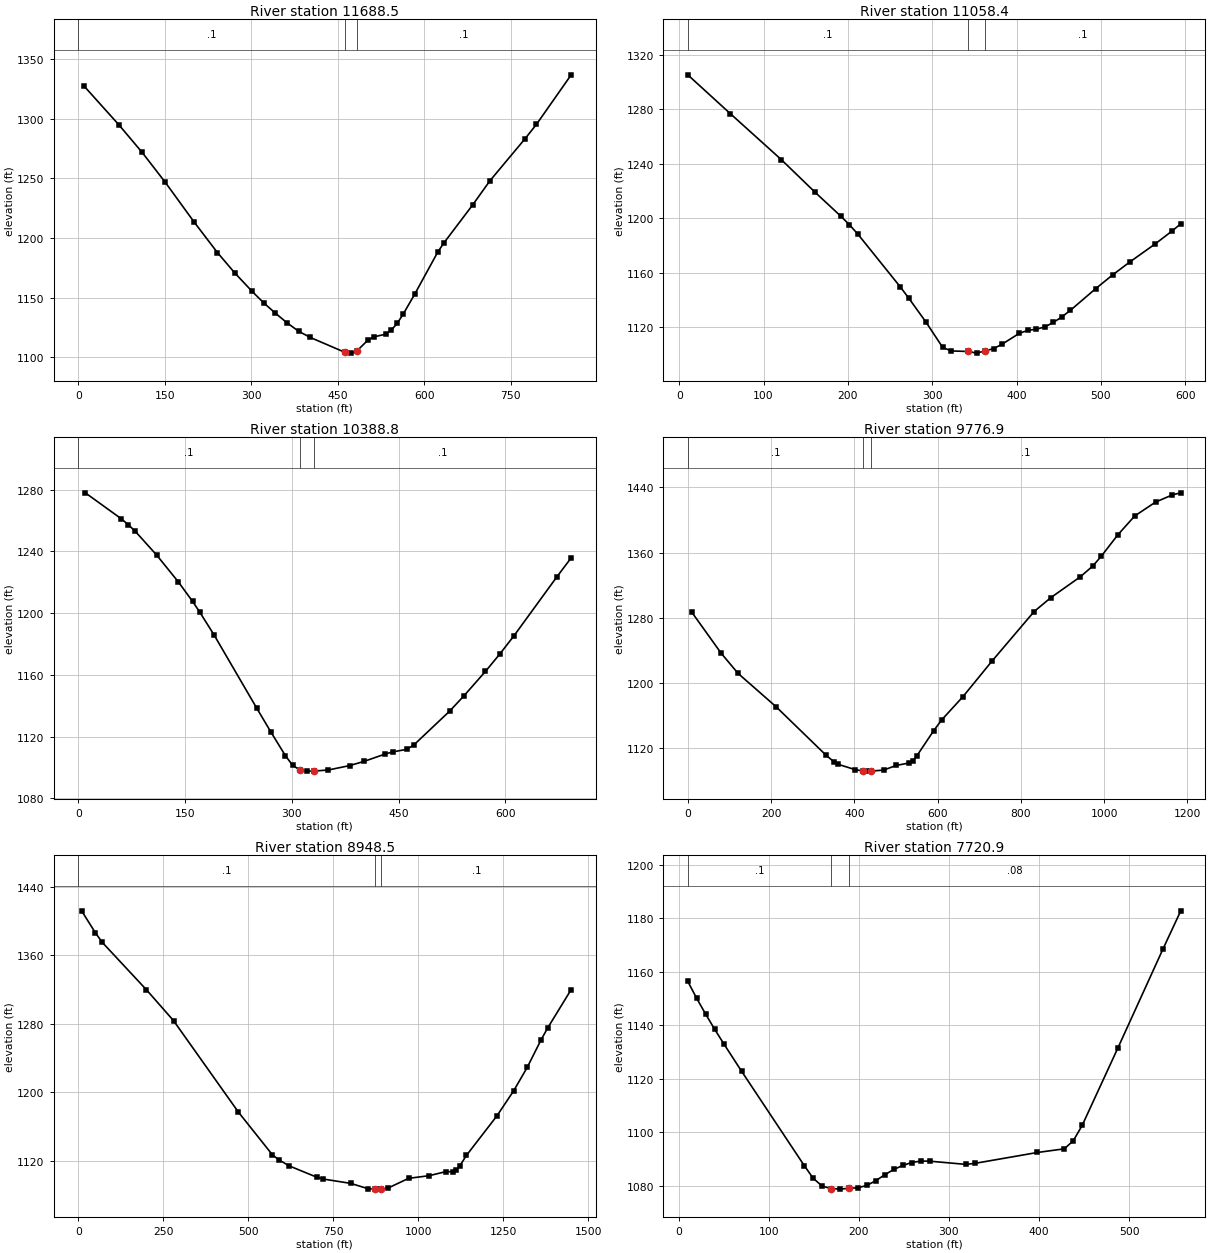
Type RM Length L Ch R = 1 ,11688.5 ,624.6,630,635.5
XS GIS Cut Line= 2
     1717108.159      157763.541     1717640.155       158432.13
#Sta/Elev= 30
    10.1 1327.67    70.4 1295.12   110.6 1272.04   150.8 1246.85     201 1213.35
   241.2  1187.8   271.4 1170.61   301.6 1155.05   321.7 1145.41   341.8 1136.82
   361.9 1128.75     382 1121.66   402.1 1116.47   462.4 1103.91   472.4 1103.27
   482.4  1104.8   502.6 1114.43   512.7 1116.97   532.8 1119.15   542.8  1122.7
   552.9 1128.32   562.9 1135.75     583 1152.61   623.2 1188.19   633.3 1195.55
   683.5 1227.69   713.7 1248.15     774 1283.13   794.1 1295.38   854.4 1337.07
#Mann= 3 , 0 , 0
       0      .1       0   462.4    .045       0   482.4      .1       0
Bank Sta=462.4,482.4
XS Rating Curve= 0 ,0
Exp/Cntr=0.3,0.1

Type RM Length L Ch R = 1 ,11058.4 ,681.3,669.7,658
XS GIS Cut Line= 2
     1716680.406      157989.999     1716906.863      158539.967
#Sta/Elev= 30
    10.1 1305.37    60.5 1276.87     121 1243.06   161.3 1218.92   191.5 1201.52
   201.6 1195.31   211.7 1188.35   262.1 1149.52   272.2 1141.21   292.3 1123.87
   312.5 1104.95   322.6  1102.4   342.8    1102  352.62 1100.79   362.8 1102.44
     373 1104.15   383.1 1107.45   403.2 1115.28   413.3 1117.54   423.4 1118.37
   433.5 1120.03   443.6 1123.31   453.6 1127.35   463.7 1132.15     494 1148.24
   514.1 1158.33   534.3 1167.76   564.5 1181.09   584.7 1190.66   594.8 1195.86
#Mann= 3 , 0 , 0
    10.1      .1       0   342.8    .045       0   362.8      .1       0
Bank Sta=342.8,362.8
XS Rating Curve= 0 ,0
Exp/Cntr=0.3,0.1

Type RM Length L Ch R = 1 ,10388.8 ,619.3,611.9,604.4
XS GIS Cut Line= 2
     1715997.438      158424.941      1716558.19      158831.127
#Sta/Elev= 30
      10 1277.99    60.2 1261.28    70.2 1257.42    80.3 1252.98   110.4 1237.54
   140.5 1220.36   160.6 1207.67   170.6 1200.78   190.7    1186   250.9 1138.33
   270.9 1122.79     291 1107.68     301  1101.5   311.1  1098.4   321.1 1097.65
   331.1 1097.69   351.2 1098.38   381.3 1101.24   401.4 1103.95   431.5 1108.79
   441.5 1110.08   461.6 1111.78   471.6 1114.68   521.8 1136.58   541.9 1146.51
     572 1162.28   592.1  1173.5   612.1 1185.39   672.3 1223.55   692.4 1235.87
#Mann= 3 , 0 , 0
       0      .1       0   311.1    .045       0   331.1      .1       0
Bank Sta=311.1,331.1
XS Rating Curve= 0 ,0
Exp/Cntr=0.3,0.1

Type RM Length L Ch R = 1 ,9776.9  ,833.1,828.4,824
XS GIS Cut Line= 4
     1715447.469      158892.235     1715681.116      159010.855
     1715972.276      159111.503     1716568.974      159255.286
#Sta/Elev= 30
    10.1 1286.47    80.6 1236.12   120.9 1211.56   211.6 1170.86   331.6 1111.34
   351.5 1102.78   361.4 1099.91   401.2 1093.49     421 1091.69     431 1091.56
     441 1091.63   470.7 1092.87   500.5 1098.55   530.3 1101.44   540.3 1104.19
   550.2  1110.4   590.2 1140.98   610.3 1154.81   660.7 1182.95   731.1 1227.04
   831.7 1287.56     872 1304.72   942.4 1330.16   972.6 1343.47   992.7 1355.33
  1032.9 1381.91  1073.2 1404.95  1123.5 1422.09  1163.8  1430.9  1183.9 1433.42
#Mann= 3 , 0 , 0
       0      .1       0     421    .045       0     441      .1       0
Bank Sta=421,441
XS Rating Curve= 0 ,0
Exp/Cntr=0.3,0.1

Type RM Length L Ch R = 1 ,8948.5  ,1214,1227.6,1240.9
XS GIS Cut Line= 4
     1715238.985      159409.852     1715853.656      159787.282
     1716184.356      159787.282     1716486.299      160046.091
#Sta/Elev= 30
      10 1411.96    50.1 1386.64    70.1 1375.45   200.4 1319.95   280.5 1283.74
   470.8 1177.25     571  1127.3   591.1 1121.11   621.1 1114.23   701.3 1101.17
   721.3 1098.92   801.5  1093.9   851.6 1087.76   871.6 1087.21   881.6  1087.2
   891.6 1087.21   911.7 1088.56   971.8  1099.8    1032 1102.88  1081.8 1107.69
  1101.7 1107.47  1111.7 1108.99  1121.6 1113.96  1141.5 1126.47    1231 1172.52
  1280.7 1202.02  1320.4 1229.26  1360.2 1260.69  1380.1    1275  1449.7 1320.09
#Mann= 3 , 0 , 0
       0      .1       0   871.6    .045       0   891.6      .1       0
Bank Sta=871.6,891.6
XS Rating Curve= 0 ,0
Exp/Cntr=0.3,0.1

Type RM Length L Ch R = 1 ,7720.9  ,623.5,620.1,616.2
XS GIS Cut Line= 2
     1714987.365      159902.308     1715422.308      160250.981
#Sta/Elev= 30
      10 1156.49    19.9 1150.13    29.9 1144.21    39.8 1138.61    49.8 1133.25
    69.7 1122.91   139.4 1087.58   149.3 1082.85   159.3 1079.92   169.2 1079.03
  179.29 1078.81   189.2 1079.13   199.1 1079.31     209 1080.22     219 1082.01
     229 1084.24   238.9 1086.17   248.9 1087.69   258.8 1088.76   268.8  1089.3
   278.7 1089.26   318.5 1088.07   328.5 1088.42   398.2 1092.51     428 1093.87
     438 1096.86   447.9 1102.61   487.8 1131.74   537.5 1168.47   557.4 1182.85
#Mann= 3 , 0 , 0
      10      .1       0   169.2    .045       0   189.2     .08       0
Bank Sta=169.2,189.2
XS Rating Curve= 0 ,0
Exp/Cntr=0.3,0.1

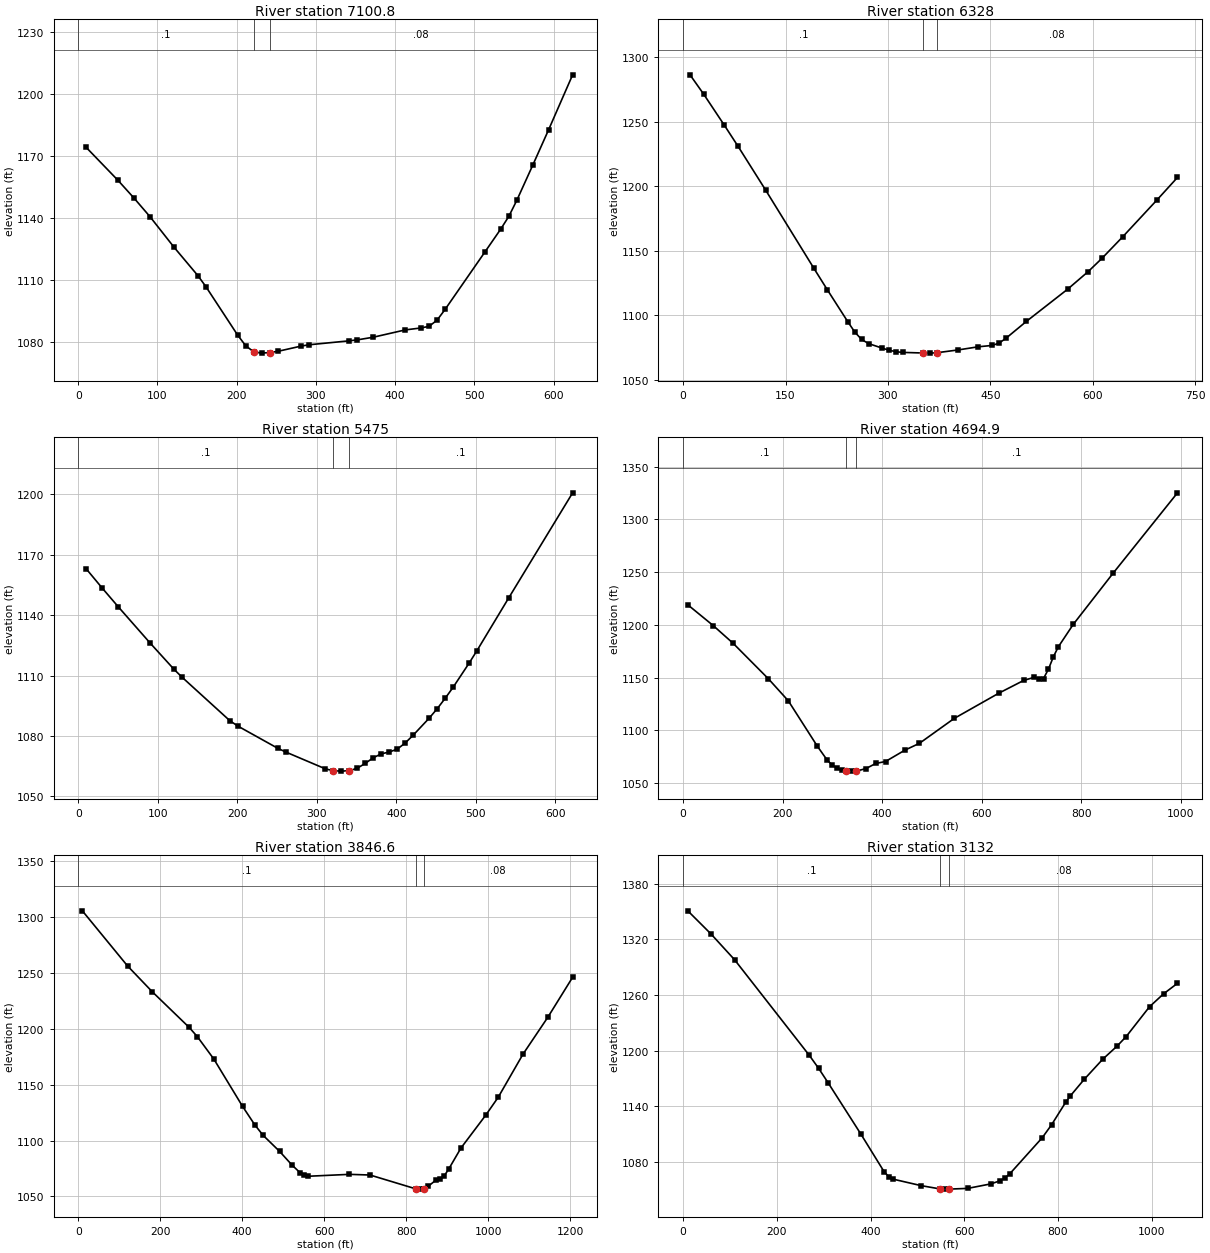
Type RM Length L Ch R = 1 ,7100.8  ,791.4,772.8,754.3
XS GIS Cut Line= 2
     1714663.854      160405.547     1715199.444      160725.463
#Sta/Elev= 30
    10.1 1174.22    50.3 1158.22    70.4 1149.67    90.6 1140.64   120.7 1125.95
   150.9 1112.13     161 1106.81   201.2 1083.25   211.3 1078.13   221.4 1075.17
   231.4 1074.54   241.4 1074.83   251.6 1075.38   281.7 1077.99   291.8 1078.61
   342.1 1080.51   352.2 1080.97   372.3 1082.25   412.6 1085.79   432.7 1086.75
   442.7 1087.53   452.8 1090.51   462.9  1095.7   513.2 1123.56   533.3 1134.73
   543.4 1140.85   553.4 1148.55   573.6 1165.65   593.7  1182.9   623.9 1209.43
#Mann= 3 , 0 , 0
       0      .1       0   221.4    .045       0   241.4     .08       0
Bank Sta=221.4,241.4
XS Rating Curve= 0 ,0
Exp/Cntr=0.3,0.1

Type RM Length L Ch R = 1 ,6328    ,853.2,853,852.7
XS GIS Cut Line= 2
     1714584.774      161397.647     1715256.957      161128.055
#Sta/Elev= 30
    10.1 1286.46    30.2 1271.42    60.4 1247.38    80.5 1231.02   120.7 1197.26
   191.1 1136.86   211.2 1119.88   241.4 1094.93   251.5 1087.05   261.5  1081.3
   271.6 1078.13   291.7 1074.58   301.8 1072.98   311.8 1071.81   321.9 1071.28
   352.1  1070.8   362.1 1070.72   372.1 1071.05   402.4 1073.16   432.5 1075.64
   452.6 1076.68   462.7 1078.44   472.8 1082.17   502.9 1095.34   563.3 1120.29
   593.5 1133.98   613.6 1144.22   643.8  1160.8   694.1 1189.42   724.2 1206.92
#Mann= 3 , 0 , 0
       0      .1       0   352.1    .045       0   372.1     .08       0
Bank Sta=352.1,372.1
XS Rating Curve= 0 ,0
Exp/Cntr=0.3,0.1

Type RM Length L Ch R = 1 ,5475    ,781.7,780.1,778.2
XS GIS Cut Line= 2
     1715019.716      162105.777     1715591.252      161861.346
#Sta/Elev= 30
      10 1162.95    30.1 1153.41    50.1  1144.2    90.2  1126.2   120.3 1113.13
   130.3 1109.25   190.5 1087.63   200.5 1084.96   250.6 1073.96   260.7 1072.09
   310.8 1063.69   320.9 1062.77   330.9 1062.57   340.9  1062.8   350.9 1064.02
   360.9 1066.43     371 1069.22     381 1071.14     391 1072.05     401 1073.46
   411.1 1076.54   421.1  1080.4   441.1 1088.79   451.2 1093.48   461.2 1098.63
   471.2  1104.1   491.3 1116.07   501.3 1122.35   541.4 1148.63   621.6 1200.67
#Mann= 3 , 0 , 0
       0      .1       0   320.9    .045       0   340.9      .1       0
Bank Sta=320.9,340.9
XS Rating Curve= 0 ,0
Exp/Cntr=0.3,0.1

Type RM Length L Ch R = 1 ,4694.9  ,815.9,848.4,880.9
XS GIS Cut Line= 4
     1715303.687      162677.313     1715504.983      162742.015
     1715738.629        162619.8     1716252.652      162551.503
#Sta/Elev= 30
    10.1 1218.77    60.4 1199.37   100.7 1182.42   171.2 1148.92   211.4 1127.95
     270  1084.7   289.6 1071.67   299.3 1067.12   309.1 1064.01   318.9 1061.98
   328.4 1061.26   338.4  1061.2   348.4 1061.25   367.7 1063.64   387.2 1068.49
   406.8 1070.32   445.8 1081.11   475.1 1087.61   544.9 1111.21   634.7  1135.2
   684.5 1147.25   704.5 1150.07   714.4  1148.9   724.4 1149.05   734.4 1158.02
   744.4 1169.88   754.3 1179.23   784.2 1200.46     864 1248.85   993.7  1325.3
#Mann= 3 , 0 , 0
       0      .1       0   328.4    .045       0   348.4      .1       0
Bank Sta=328.4,348.4
XS Rating Curve= 0 ,0
Exp/Cntr=0.3,0.1

Type RM Length L Ch R = 1 ,3846.6  ,710.5,714.6,718.9
XS GIS Cut Line= 4
      1715195.85      162774.366     1715738.629      163169.768
     1715864.439      163399.821     1716098.086      163540.009
#Sta/Elev= 30
      10 1305.46   120.3 1256.15   180.4 1233.15   270.6 1201.21   290.7 1192.87
   330.8  1172.9   400.9 1130.57     431 1113.92     451  1104.7   491.1 1090.39
   521.2 1078.24   541.2 1071.25   551.3 1069.14   561.3  1068.1   661.5 1069.79
   711.9  1069.2   822.9  1056.9   832.9 1056.58   842.9 1056.99   853.1 1058.97
   873.2 1064.75   883.3 1065.63   893.4 1068.72   903.5 1074.29   933.7 1093.32
   994.3 1122.75  1024.6 1138.71  1085.1 1177.26  1145.7 1210.28  1206.2 1246.05
#Mann= 3 , 0 , 0
       0      .1       0   822.9    .045       0   842.9     .08       0
Bank Sta=822.9,842.9
XS Rating Curve= 0 ,0
Exp/Cntr=0.3,0.1

Type RM Length L Ch R = 1 ,3132    ,657.4,644.2,630.7
XS GIS Cut Line= 4
     1714926.257      162709.664     1715048.473      163047.553
     1715152.715      163399.821     1715350.416      163662.224
#Sta/Elev= 30
      10 1350.88    59.9 1325.71   109.8 1298.13   269.5 1194.87   289.4 1180.83
   309.4 1165.44   379.2  1110.2   428.8 1069.61   438.7 1064.15   448.7 1061.34
   508.2 1054.39   547.9  1050.9   557.9 1050.64   567.9 1050.66   607.5 1051.44
   657.2 1056.33     677 1059.75     687 1062.75   696.9 1066.96   766.5 1106.08
   786.4 1120.03   816.3 1144.14   826.2 1151.03   856.1 1169.06   895.9 1190.92
   925.8 1204.71   945.7 1215.23   995.5 1247.39  1025.4 1261.29  1055.2  1272.7
#Mann= 3 , 0 , 0
       0      .1       0   547.9    .045       0   567.9     .08       0
Bank Sta=547.9,567.9
XS Rating Curve= 0 ,0
Exp/Cntr=0.3,0.1

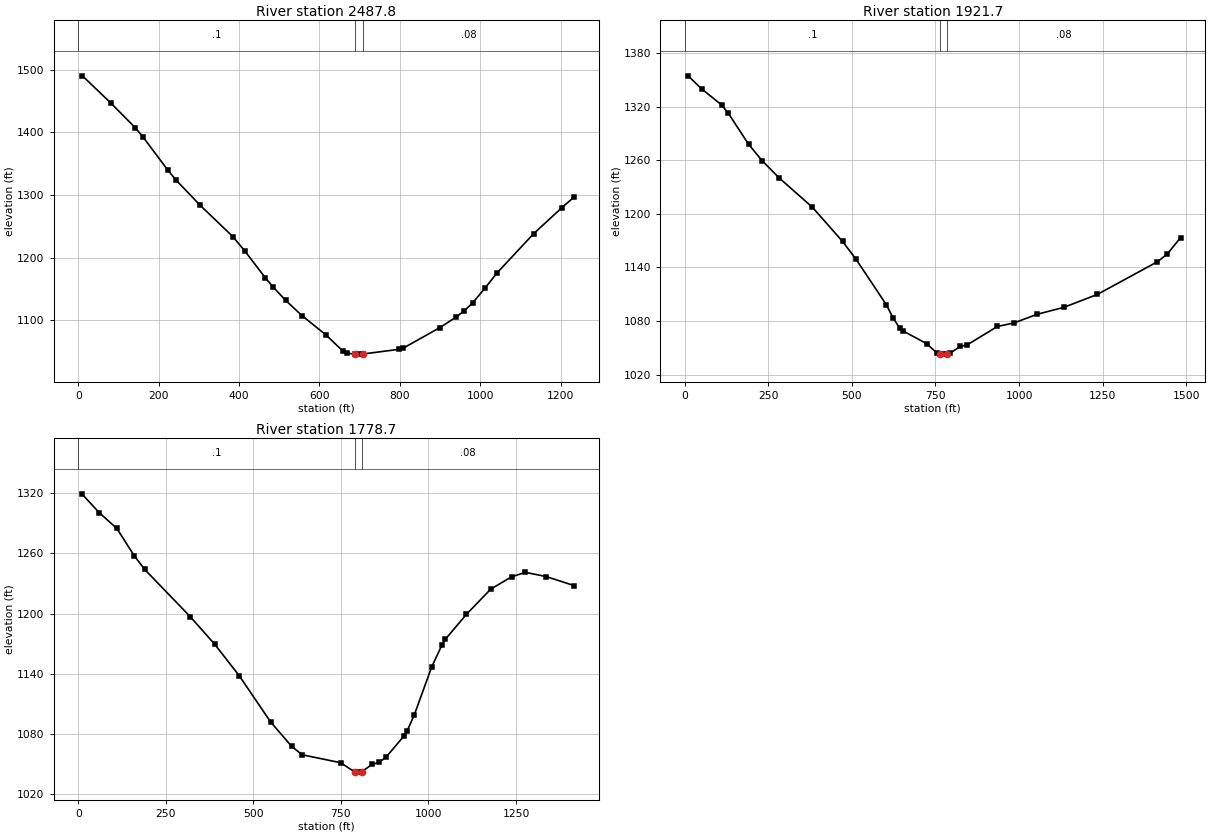
Type RM Length L Ch R = 1 ,2487.8  ,565.6,566.1,566.6
XS GIS Cut Line= 2
     1714063.562      163173.363     1715044.878      163921.033
#Sta/Elev= 30
    10.1 1490.19    80.9 1446.71   141.6 1407.34   161.8 1391.78   222.5 1339.72
   242.7 1323.99   303.4 1283.29   384.3 1233.47   414.6 1210.18   465.2 1167.69
   485.4 1152.39   515.7  1131.7   556.2 1107.37   616.8 1076.06   657.3 1051.17
   667.4 1047.34   687.7 1045.76   697.7 1045.73   707.7  1045.9   798.9 1053.49
     809  1055.5     900 1088.23   940.4 1105.15   960.7 1115.15   980.9 1127.41
  1011.2 1150.58  1041.6 1175.31  1132.6 1237.86  1203.4 1279.78  1233.7 1296.65
#Mann= 3 , 0 , 0
       0      .1       0   687.7    .045       0   707.7     .08       0
Bank Sta=687.7,707.7
XS Rating Curve= 0 ,0
Exp/Cntr=0.3,0.1

Type RM Length L Ch R = 1 ,1921.7  ,140,143,146
XS GIS Cut Line= 4
     1713901.798      163457.317     1714197.872       163970.57
     1714441.702      164166.346     1714913.192      164500.977
#Sta/Elev= 30
      10 1354.77    50.2 1340.19   110.5 1322.06   130.6  1312.6   190.8 1278.15
     231 1259.85   281.2 1240.74   381.6 1207.57     472 1169.18   512.2 1149.29
   602.6 1098.52   622.8 1083.73     643 1072.07     653 1068.88   723.7 1054.65
   753.9 1044.31   764.1    1043   774.1 1042.93   784.1 1043.22   794.3  1044.2
   824.5 1051.58   844.7 1053.27   935.1  1073.9     985 1077.92  1054.8 1087.64
  1134.5 1095.39  1234.2 1109.81  1413.6 1146.37  1443.5 1155.05  1483.4 1173.59
#Mann= 3 , 0 , 0
       0      .1       0   764.1    .045       0   784.1     .08       0
Bank Sta=764.1,784.1
XS Rating Curve= 0 ,0
Exp/Cntr=0.3,0.1

Type RM Length L Ch R = 1 ,1778.7  ,1800.1,1778.7,1757.4
XS GIS Cut Line= 4
     1713830.666       163523.18     1714145.574      164079.317
      1714328.68      164278.117     1714726.281      164592.013
#Sta/Elev= 30
      10 1319.21    59.9 1300.36   109.8 1284.84   159.8 1257.49   189.7 1243.88
   319.6 1196.93   389.5 1169.43   459.4  1138.2   549.2 1092.07   609.1 1067.88
   639.1 1059.45   749.2 1051.55   789.3 1042.29   799.3 1042.17   809.3 1042.76
   839.3 1049.84   859.3 1051.91   879.4  1057.3   929.2 1077.86   939.2 1083.43
     959 1098.72  1008.7 1146.48  1038.5 1168.83  1048.4 1174.51    1108 1199.13
  1177.6  1224.3  1237.2  1236.6  1276.9 1241.05  1336.5 1236.81    1416 1227.85
#Mann= 3 , 0 , 0
       0      .1       0   789.3    .045       0   809.3     .08       0
Bank Sta=789.3,809.3
XS Rating Curve= 0 ,0
Exp/Cntr=0.3,0.1
Stream Node=Panther Creek   ,Main            , 0 , 0 ,Upstream end
Stream Node=Panther Creek   ,Main            , 0 , 1 ,Downstream end

Chan Stop Cuts=-1
Use User Specified Reach Order=0